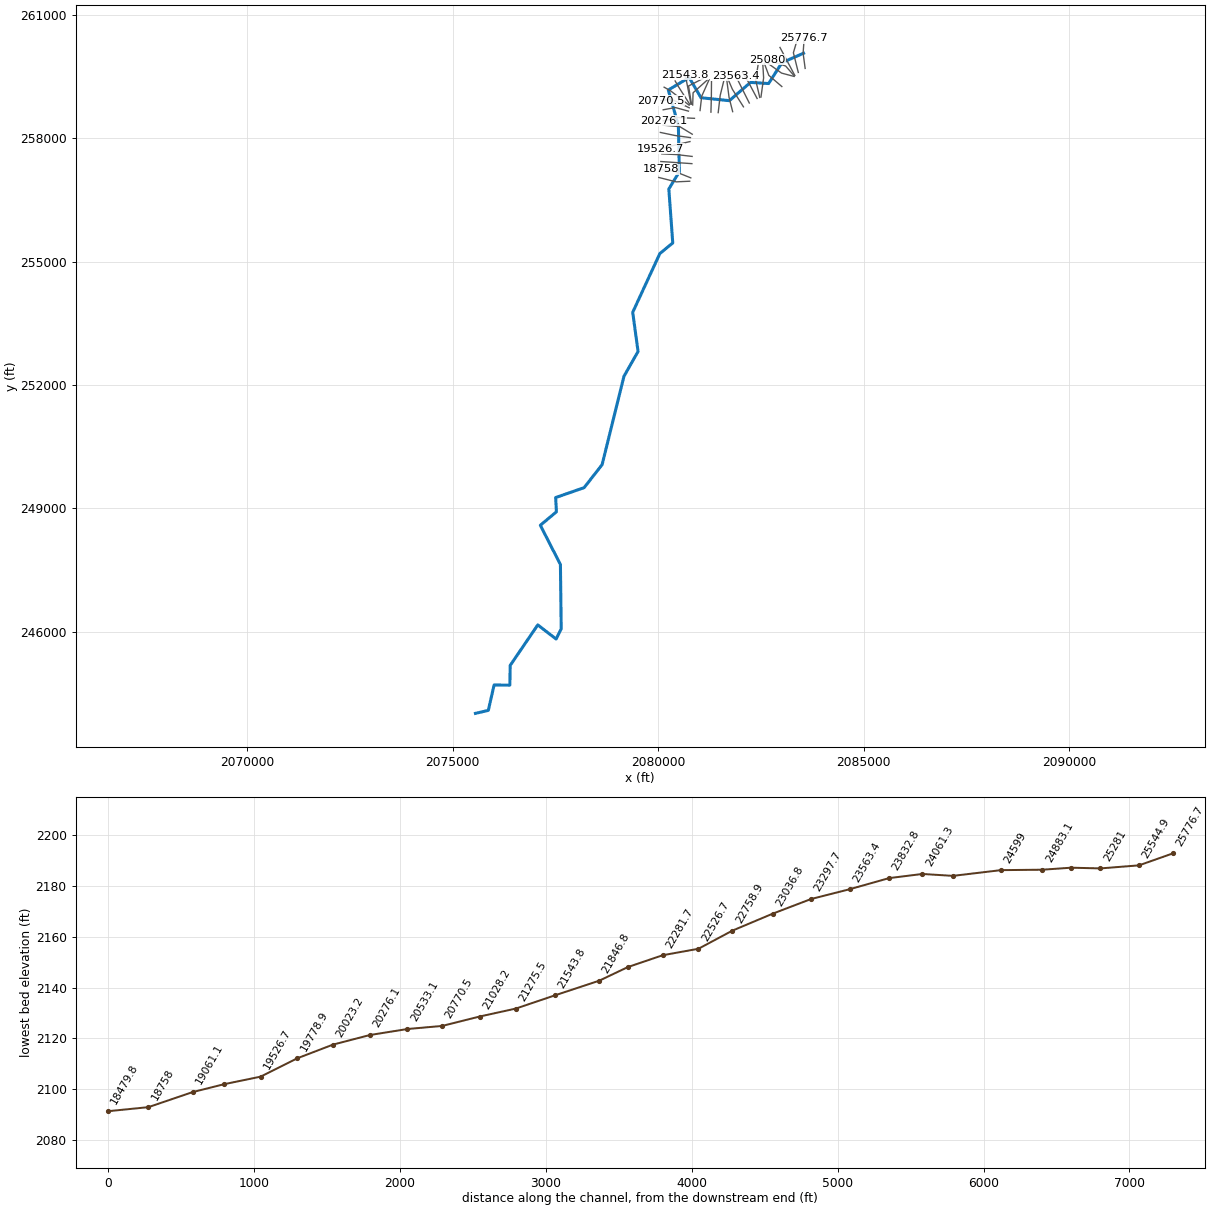
--- LAURELCK4.prj (project) ---

Proj Title=LAURELCK4
Current Plan=p01
Default Exp/Contr=0,0
English Units
Geom File=g01
Flow File=f01
Plan File=p01
BEGIN DESCRIPTION:
END DESCRIPTION:
DSS Export Rating Curves= 0
DSS Export Rating Curve Sorted= 0
DSS Export Volume Flow Curves= 0
DXF OffsetX= 0
DXF OffsetY= 0
DXF ScaleX= 0
DXF ScaleY= 0

--- LAURELCK4.p01 (plan) ---

Plan Title=Floodplain
Program Version=4.00
Geom File=g01
Flow File=f01
K Sum by GR=0
Std Step Tol=0.01
Critical Tol=0.01
Num of Std Step Trials=20
Max Error Tol=0.3
Flow Tol Ratio=0.001
Split Flow NTrial=30
Split Flow Tol=0.02
Split Flow Ratio=0.02
Log Output Level=0
Friction Slope Method=1
Unsteady Friction Slope Method=2
Unsteady Bridges Friction Slope Method=1
Global Log Level=0
CheckData=False
Run HTab=0
Run UNet=0
Run PostProcess=0
UNET Theta=0
UNET Theta Warmup=0
UNET ZTol=0
UNET ZSATol=0
UNET MxIter=0
UNET MaxInSteps=0
UNET DtIC=0
UNET DtMin=0
UNET MaxCRTS=0
UNET WFStab=0
UNET SFStab=0
UNET WFX=0
UNET SFX=0
UNET DSS MLevel=0
UNET DZMax Abort=0
UNET Convert EG Bridges=0
UNET Use Existing IB Tables=0
UNET Froude Limit=0
UNET Froude Power=0
Write IC File=0
Echo Input=False
Echo Output=False
Write Detailed=0

--- LAURELCK4.f01 (steady flow) ---

Flow Title=NFF Regression Equation
Program Version=4.10
Number of Profiles= 1
Profile Names=P100yr
River Rch & RM=LAURELCK4,Main            ,25776.7
509.7725
River Rch & RM=LAURELCK4,Main            ,23563.4
531.9171
River Rch & RM=LAURELCK4,Main            ,17756
 589.722
River Rch & RM=LAURELCK4,Main            ,17273.6
722.4501
River Rch & RM=LAURELCK4,Main            ,15313.6
737.8326
River Rch & RM=LAURELCK4,Main            ,15009.3
1039.933
River Rch & RM=LAURELCK4,Main            ,13815.3
1071.588
River Rch & RM=LAURELCK4,Main            ,11289.4
1161.263
River Rch & RM=LAURELCK4,Main            ,9019.4
 1286.65
River Rch & RM=LAURELCK4,Main            ,5225
1339.899
River Rch & RM=LAURELCK4,Main            ,353.8
1482.608
River Rch & RM=LAURELCK4,Main            ,278
1484.147
Boundary for River Rch & Prof#=LAURELCK4,Main            , 1
Up Type= 0
Dn Type= 3
Dn Slope=0.007
DSS Import GetInterval= 0
DSS Import GetPeak= 0
DSS Import FillOption= 0

--- LAURELCK4.g01 (geometry) ---

Geom Title=USGS 1m DEM
Program Version=4.10

River Reach=LAURELCK4       ,Main
Reach XY= 30
      2083538.12      260063.786     2083014.032      259834.836
     2082688.511      259327.024     2082247.973       259354.15
      2081733.65      258910.357     2081043.546      258981.972
     2080756.002      259473.508     2080248.189      259169.689
     2080493.415      258311.399     2080517.287      257182.927
      2080261.21       256764.09     2080356.696      255451.155
     2080043.111      255195.079     2079382.304      253764.958
     2079512.512      252813.352     2079169.631      252210.053
     2078637.947      250061.616     2078200.663      249502.805
     2077508.389       249261.92     2077525.677      248913.711
     2077134.908      248587.657     2077623.624      247634.532
     2077642.721      246071.164     2077519.457      245822.032
     2077072.408      246164.914     2076401.401      245180.539
     2076393.589      244701.373     2076009.908      244704.845
     2075869.283      244087.658     2075555.416      244015.018

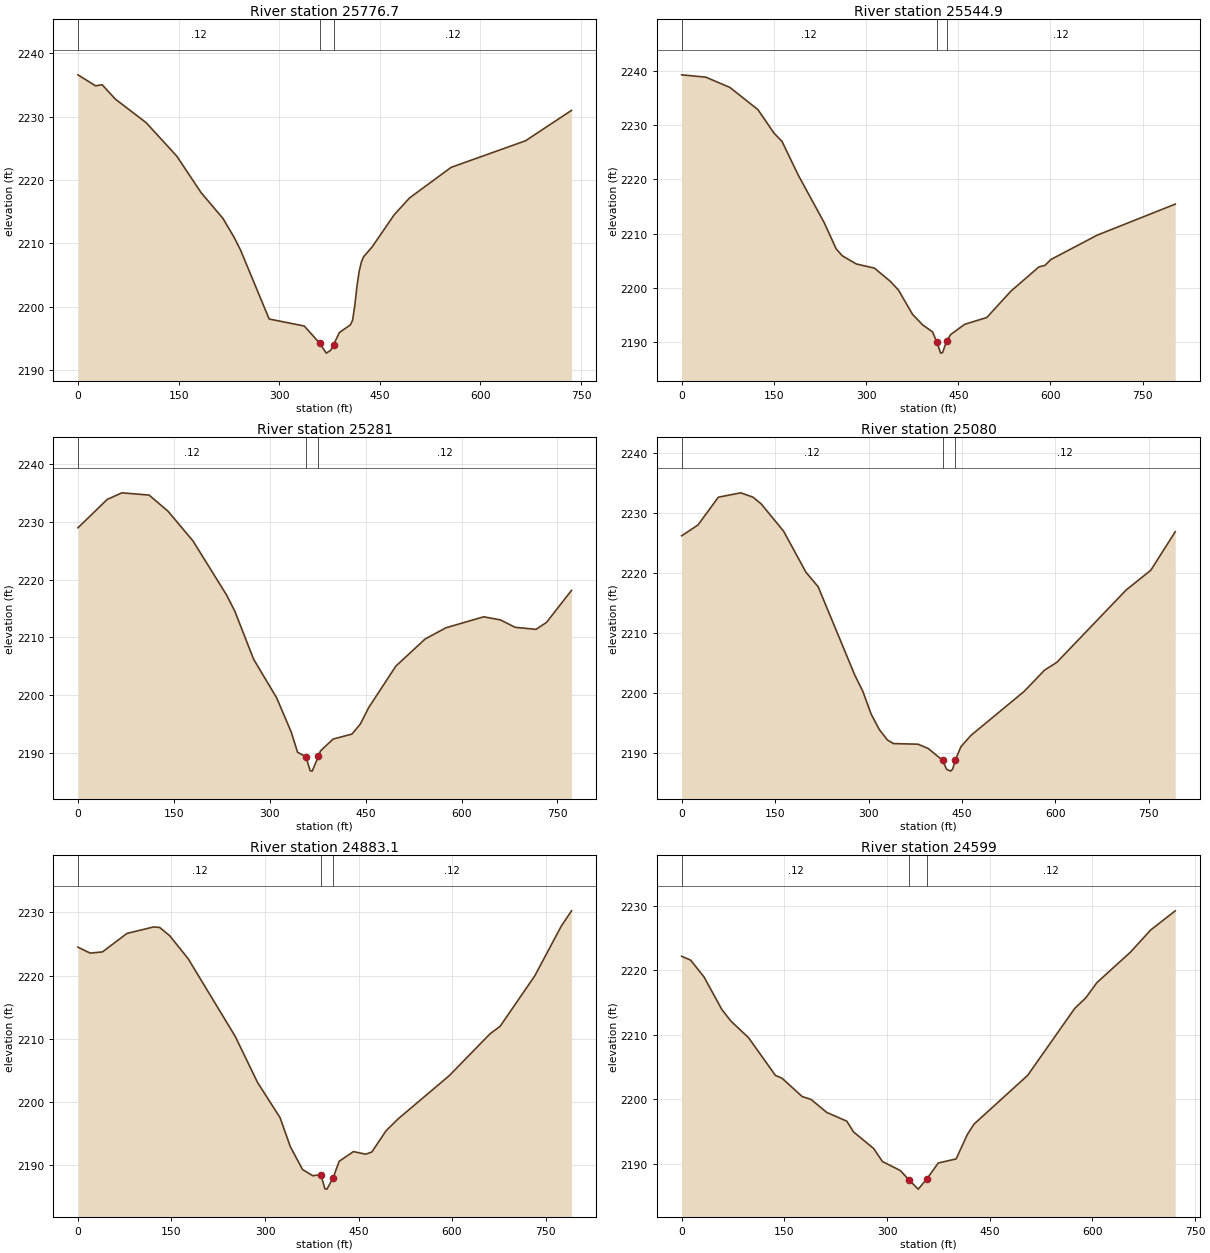
Type RM Length L Ch R = 1 ,25776.7 ,227.3,231.9,243
XS GIS Cut Line= 3
     2083578.087      259694.359     2083528.146      260064.498
     2083553.962      260425.902
#Sta/Elev= 30
       0  2236.6    26.2 2234.86      36 2235.04    55.7 2232.77   101.6 2229.05
   147.4 2223.75   183.5 2218.01   216.2 2213.92   232.6 2210.98   242.4 2208.93
     285 2198.05   337.4 2196.94   360.4 2194.22   370.2 2192.66   376.8 2193.11
     381 2193.99   389.8 2195.92   406.1 2197.12   409.4 2197.84   412.7 2200.18
   415.9 2203.21   419.2 2205.57   422.5 2207.04   425.7 2207.85   438.8 2209.47
   471.4  2214.5   494.3 2217.16   556.3 2221.99   667.3 2226.19   735.8 2230.99
#Mann= 3 ,-1 , 0
       0     .12       0   360.4    .045       0     381     .12       0
Bank Sta=360.4,381
XS Rating Curve= 0 ,0
Exp/Cntr=0.3,0.1

Type RM Length L Ch R = 1 ,25544.9 ,255.1,263.9,265.4
XS GIS Cut Line= 3
     2083411.214       259596.82     2083291.621      260075.194
     2083378.892      260372.562
#Sta/Elev= 30
       0 2239.26    39.2 2238.83    78.4 2236.94   124.1 2232.84   150.2 2228.52
   163.3 2226.97   189.4 2220.83   231.8 2212.03   251.4 2207.18   261.2 2205.92
   284.1  2204.4   313.5 2203.64   339.6 2201.19   352.7 2199.59   375.5 2195.13
   391.9 2193.19   408.2 2191.88   414.7 2190.11   421.3 2187.97   424.5 2188.06
     431 2190.21   437.6 2191.39   460.4 2193.28   496.4 2194.53   535.5 2199.38
   581.2 2203.86     591 2204.14   600.8 2205.23   675.8  2209.7     803 2215.43
#Mann= 3 ,-1 , 0
       0     .12       0   414.7    .045       0     431     .12       0
Bank Sta=414.7,431
XS Rating Curve= 0 ,0
Exp/Cntr=0.3,0.1

Type RM Length L Ch R = 1 ,25281   ,172.4,201,229.2
XS GIS Cut Line= 2
     2083327.176      259522.477     2082965.162      260204.485
#Sta/Elev= 30
       0 2229.01    45.8 2233.94    68.7 2235.08   111.2 2234.69   140.7 2231.91
     180 2226.72   232.3 2217.38   245.4 2214.53   274.8 2206.19   310.8  2199.5
   333.7 2193.53   343.5 2190.05   356.6 2189.27   363.2 2186.85   366.4 2186.77
   376.2 2189.34   379.5  2190.3   399.2 2192.34   428.6  2193.2   441.7 2194.94
   454.8  2197.8   497.3    2205   543.1 2209.71   575.8 2211.66   634.7 2213.56
   660.9 2213.02   683.8 2211.74   716.5 2211.38   732.9 2212.58   772.1 2218.15
#Mann= 3 ,-1 , 0
       0     .12       0   356.6    .045       0   376.2     .12       0
Bank Sta=356.6,376.2
XS Rating Curve= 0 ,0
Exp/Cntr=0.3,0.1

Type RM Length L Ch R = 1 ,25080   ,208.5,196.9,183.2
XS GIS Cut Line= 3
     2083312.757      259513.111     2083104.149      259751.968
     2082655.027      259907.214
#Sta/Elev= 30
       0 2226.27    26.2 2228.08    58.8  2232.7    94.8 2233.43   114.4 2232.71
   127.5  2231.6   163.5 2227.05   199.4 2220.21     219 2217.79   277.9 2203.05
     291  2200.3     304 2196.58   317.1    2194   330.2 2192.25   340.1 2191.64
   379.4 2191.54   395.8 2190.82   418.7 2188.87   425.3 2187.36   431.8 2187.05
   435.1 2187.41   439.4 2188.95   448.2 2191.11   464.6 2193.03   549.8 2200.34
   582.6 2203.89   602.2 2205.18   713.7 2217.26     753 2220.52   792.3 2226.95
#Mann= 3 ,-1 , 0
       0     .12       0   418.7    .045       0   439.4     .12       0
Bank Sta=418.7,439.4
XS Rating Curve= 0 ,0
Exp/Cntr=0.3,0.1

Type RM Length L Ch R = 1 ,24883.1 ,281.8,284.1,275.4
XS GIS Cut Line= 3
     2083307.782      259499.852     2083003.949      259580.658
     2082615.641       259858.23
#Sta/Elev= 30
       0 2224.49    19.6 2223.55    39.3 2223.74    78.6 2226.66   121.2 2227.68
     131 2227.61   147.4 2226.27   176.8 2222.66   252.2  2210.4   288.2 2203.09
   324.2 2197.55   340.6 2192.98   360.2 2189.36   376.5 2188.38   389.6 2188.54
   396.1 2186.32   399.4 2186.26   409.2 2188.03     419 2190.66   441.9 2192.19
   461.5 2191.78   471.3 2192.12   494.2 2195.48   513.8 2197.38   595.6 2204.19
   660.9 2210.79   677.3    2212   732.9 2219.98   775.4 2227.84   791.7 2230.23
#Mann= 3 ,-1 , 0
       0     .12       0   389.6    .045       0   409.2     .12       0
Bank Sta=389.6,409.2
XS Rating Curve= 0 ,0
Exp/Cntr=0.3,0.1

Type RM Length L Ch R = 1 ,24599   ,363.1,328.7,288.8
XS GIS Cut Line= 3
     2083010.414        259254.2     2082693.652       259525.71
     2082586.988      259810.149
#Sta/Elev= 30
       0 2222.17      13 2221.59    32.6 2218.98    58.7 2213.92    71.7 2212.16
    97.8 2209.54   136.9 2203.72   146.7 2203.27     176 2200.44     189 2199.99
   211.9 2197.98   241.2 2196.62     251 2194.96   280.3  2192.4   293.3 2190.37
   319.4 2188.97   332.5 2187.47   345.5 2186.09   357.8 2187.62   374.8 2190.14
   400.9 2190.77   417.2 2194.53     427 2196.16   505.4 2203.72     574 2214.08
   590.3 2215.73   606.6  2218.1   655.6 2222.82     685 2226.24     721 2229.22
#Mann= 3 ,-1 , 0
       0     .12       0   332.5    .045       0   357.8     .12       0
Bank Sta=332.5,357.8
XS Rating Curve= 0 ,0
Exp/Cntr=0.3,0.1

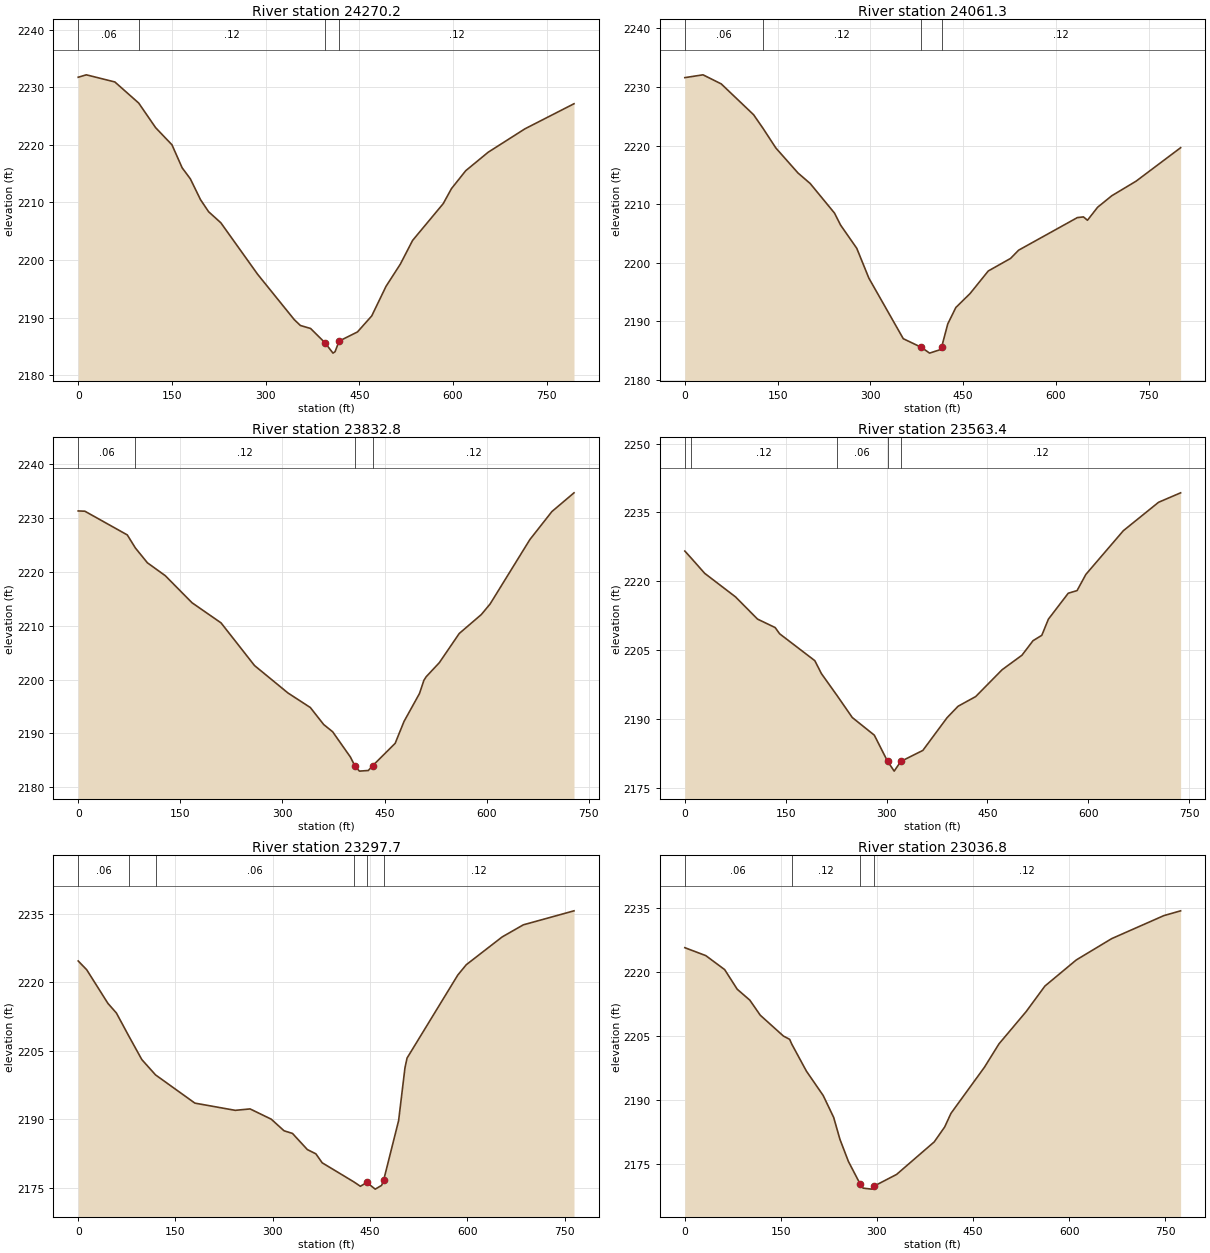
Type RM Length L Ch R = 1 ,24270.2 ,197.6,208.9,210
XS GIS Cut Line= 3
     2082502.949      258998.851     2082567.594      259464.297
       2082548.2      259787.523
#Sta/Elev= 30
       0 2231.73      13 2232.15    58.7 2230.91   96.892227.244     124 2222.97
   150.1    2220   166.4 2216.01   179.5  2214.1   195.8 2210.48   208.8 2208.38
   228.4 2206.46   287.2 2197.53   345.9 2189.65   355.7 2188.64     372 2188.12
   394.9 2185.66   407.9 2183.84   411.2 2184.09   417.7 2185.93   447.1 2187.52
   469.9  2190.3   492.8 2195.44   515.7 2199.29   535.3  2203.4   584.4  2209.8
   597.5 2212.39   620.4 2215.51   656.4 2218.72   715.2 2222.78   793.7 2227.13
#Mann= 4 ,-1 , 0
       0     .06       0   96.89     .12       0   394.9    .045       0
   417.7     .12       0
Bank Sta=394.9,417.7
XS Rating Curve= 0 ,0
Exp/Cntr=0.3,0.1

Type RM Length L Ch R = 1 ,24061.3 ,198.8,228.5,223.2
XS GIS Cut Line= 3
     2082473.221      258989.095     2082373.658      259415.813
     2082431.839      259774.594
#Sta/Elev= 30
       0 2231.61    29.4 2232.09    58.9 2230.54   111.2 2225.28  126.542222.939
   147.2  2219.6   183.1 2215.32   202.7 2213.54     242 2208.49   251.8 2206.45
     278 2202.48   297.6 2197.38   353.2 2187.05   382.6 2185.57   395.7 2184.59
     412 2185.15   415.3 2185.66   425.1 2189.57   438.2 2192.38   461.1 2194.75
   490.6 2198.61   526.6 2200.75   539.7 2202.16   634.6 2207.72   644.5 2207.84
     651 2207.27   667.4 2209.49   690.3 2211.45   729.6 2213.94   801.6 2219.65
#Mann= 4 ,-1 , 0
       0     .06       0  126.54     .12       0   382.6    .045       0
   415.3     .12       0
Bank Sta=382.6,415.3
XS Rating Curve= 0 ,0
Exp/Cntr=0.3,0.1

Type RM Length L Ch R = 1 ,23832.8 ,268.3,269.4,262
XS GIS Cut Line= 3
     2082409.098      258963.581     2082186.187       259383.49
     2082050.432       259596.82
#Sta/Elev= 30
       0 2231.36     9.8 2231.31    72.1  2226.9   83.992224.472   101.6 2221.72
   127.9 2219.32   167.2 2214.28   209.8 2210.54     259  2202.6   308.2 2197.49
     341 2194.79   360.6 2191.63   373.8 2190.28     400 2185.55   406.6 2183.89
   413.1 2182.96   426.2 2183.08   432.8    2184   465.6 2188.13   478.6  2192.2
   501.3 2197.39   507.8 2199.85   511.1 2200.51   530.5 2203.14   559.7 2208.56
   592.1 2212.08   605.1 2214.06   663.4 2226.02   695.8 2231.24   728.3 2234.73
#Mann= 4 ,-1 , 0
       0     .06       0   83.99     .12       0   406.6    .045       0
   432.8     .12       0
Bank Sta=406.6,432.8
XS Rating Curve= 0 ,0
Exp/Cntr=0.3,0.1

Type RM Length L Ch R = 1 ,23563.4 ,260.6,265.7,269
XS GIS Cut Line= 2
      2082218.51      258853.399     2081888.819      259512.781
#Sta/Elev= 30
       0 2226.57    8.992225.119    29.5 2221.72    75.4 2216.58   108.1 2211.74
   134.3  2209.9   140.9 2208.55   193.3 2202.68   203.1 2199.86  226.322195.089
     249 2190.29   281.8 2186.44   301.4 2180.77   311.3 2178.61   321.1 2180.72
   353.9 2183.12   389.9 2190.25   406.3 2192.75   432.5 2194.86   471.8 2200.71
   501.3 2203.87   517.7 2207.03   530.8 2208.21   540.6 2211.73   570.1 2217.38
   583.2 2217.95   596.3 2221.48     652    2231   704.4  2237.2   737.2 2239.26
#Mann= 5 ,-1 , 0
       0     .06       0    8.99     .12       0  226.32     .06       0
   301.4    .045       0   321.1     .12       0
Bank Sta=301.4,321.1
XS Rating Curve= 0 ,0
Exp/Cntr=0.3,0.1

Type RM Length L Ch R = 1 ,23297.7 ,270.4,260.9,245.8
XS GIS Cut Line= 3
      2082077.05      258760.384     2081808.012      259186.322
      2081704.58       259425.51
#Sta/Elev= 30
       0 2224.69    13.1 2222.77    45.8 2215.41    58.9  2213.3   77.742208.331
    98.1  2203.1  119.182199.756   179.9 2193.57   242.1 2191.99     265  2192.3
   297.7 2190.05   317.3 2187.52   330.4 2186.93   353.3  2183.4   366.4 2182.47
   376.2  2180.5  424.672176.355   435.1 2175.36   444.9  2176.2     458 2174.74
   467.8 2175.56   471.1  2176.8     494 2189.74   503.8 2201.31     507 2203.43
   585.2  2221.6   598.3 2223.87   653.6 2229.95   686.2  2232.6   764.4 2235.67
#Mann= 6 ,-1 , 0
       0     .06       0   77.74     .12       0  119.18     .06       0
  424.67     .12       0   444.9    .045       0   471.1     .12       0
Bank Sta=444.9,471.1
XS Rating Curve= 0 ,0
Exp/Cntr=0.3,0.1

Type RM Length L Ch R = 1 ,23036.8 ,289.5,277.9,266.1
XS GIS Cut Line= 3
     2081814.477      258643.302     2081727.206      258985.922
     2081672.257      259402.884
#Sta/Elev= 30
       0 2225.76    32.7  2223.9    62.2 2220.61    81.8    2216   101.5 2213.43
   117.8 2209.89   153.9    2205   163.7 2204.22  166.912203.121   189.9 2196.74
   216.1 2191.01   232.4 2185.88   242.2 2180.72   255.4 2175.54   274.1 2170.13
   278.3 2169.27   291.4 2169.03   294.6 2169.67   330.6 2172.48   389.4 2180.13
   405.7 2183.63   415.5 2186.83   467.7 2197.65   490.5 2203.16   532.9 2210.74
   562.2 2216.74   611.1 2222.87   666.5 2227.89     748  2233.3   774.1 2234.42
#Mann= 4 ,-1 , 0
       0     .06       0  166.91     .12       0   274.1    .045       0
   294.6     .12       0
Bank Sta=274.1,294.6
XS Rating Curve= 0 ,0
Exp/Cntr=0.3,0.1

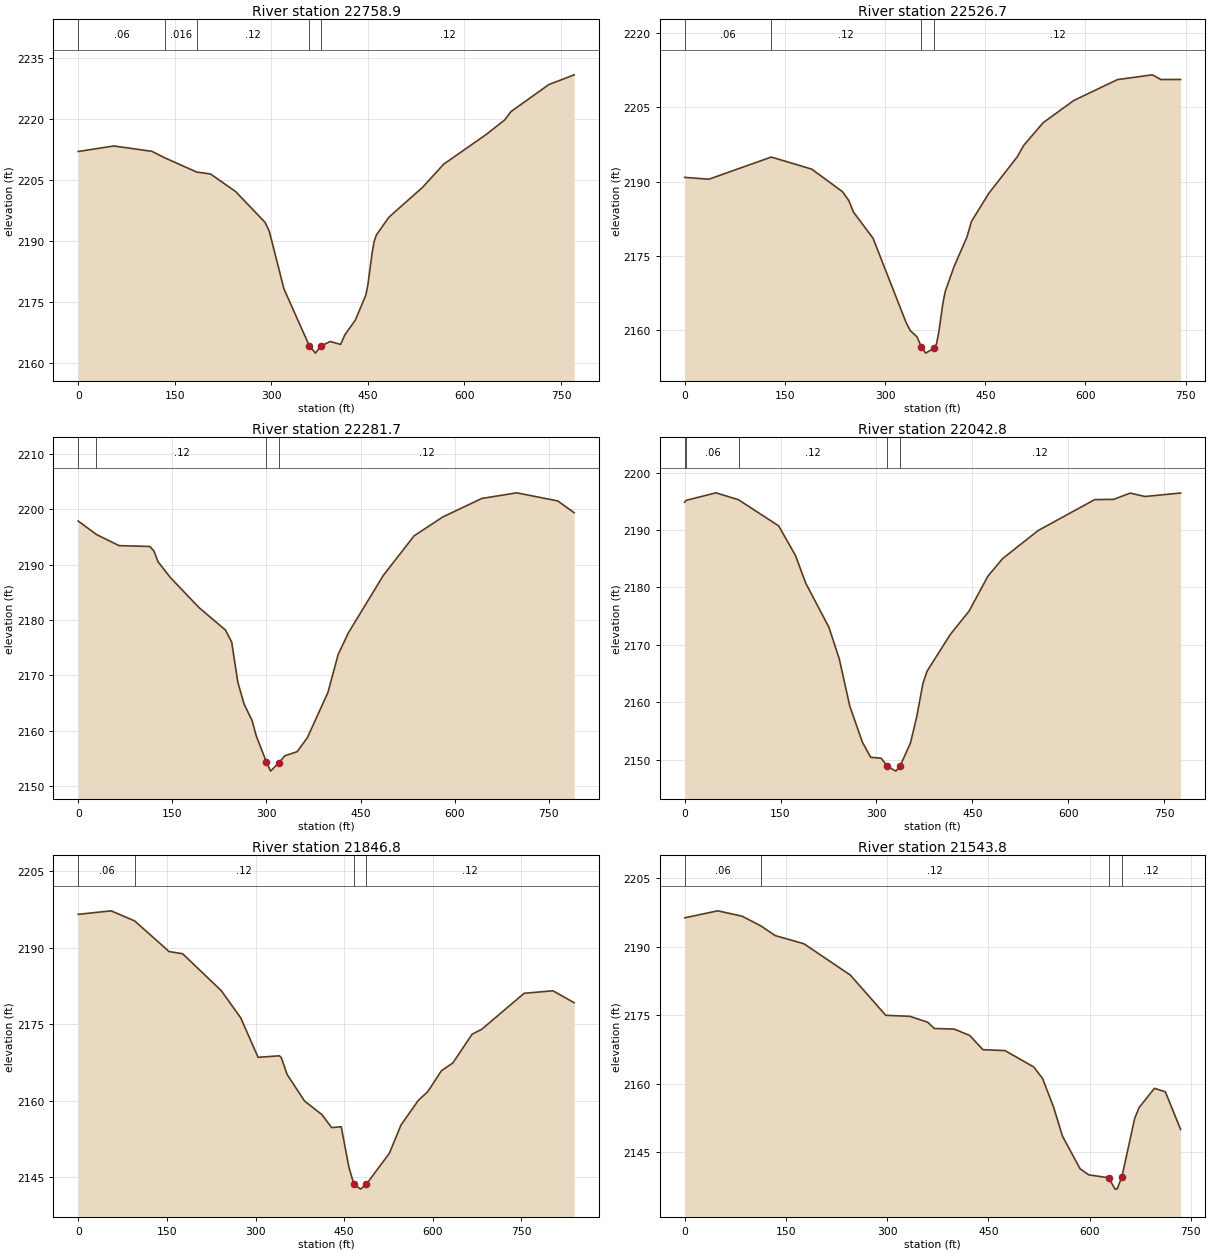
Type RM Length L Ch R = 1 ,22758.9 ,210.8,232.1,229
XS GIS Cut Line= 3
     2081462.451      258619.691     2081510.644      259037.638
     2081594.683      259377.026
#Sta/Elev= 30
       0 2211.98    55.4 2213.34   114.2 2212.03  134.832210.397  184.172206.912
   205.5 2206.45   244.6  2202.1   290.3 2194.53   296.8 2192.36   319.6 2178.15
   358.8  2164.2   368.5 2162.33   376.9 2164.04   391.4  2165.2   407.7 2164.47
   414.2 2166.84   430.5 2170.46   446.9 2176.67   450.1 2179.27   456.7 2187.14
   459.9 2189.93   463.2 2191.43   482.8 2195.83   535.1 2203.18   567.8 2208.87
   633.1 2216.09   662.5 2219.74   672.3 2221.81   731.1 2228.46   770.4 2230.86
#Mann= 5 ,-1 , 0
       0     .06       0  134.83    .016       0  184.17     .12       0
   358.8    .045       0   376.9     .12       0
Bank Sta=358.8,376.9
XS Rating Curve= 0 ,0
Exp/Cntr=0.3,0.1

Type RM Length L Ch R = 1 ,22526.7 ,248.4,245.1,242.3
XS GIS Cut Line= 3
     2081285.621      258631.224     2081295.876      258995.027
     2081299.162      259373.436
#Sta/Elev= 30
       0 2190.84    36.1 2190.46  129.672194.956   190.2 2192.51   236.1 2187.95
   245.9  2186.1   252.5 2183.84     282  2178.5   331.2  2161.5   337.7 2159.79
   347.6 2158.55   354.1 2156.56   360.7 2155.22   373.7 2156.25     377 2157.12
   380.3  2159.4   386.8 2165.54     390  2167.7   403.1 2172.71   422.7  2178.8
   429.2 2181.88   455.3 2187.61   497.7 2194.97   507.5 2197.32   536.8 2201.94
   582.5 2206.42   647.8 2210.65     700 2211.62     713 2210.67   742.4 2210.68
#Mann= 4 ,-1 , 0
       0     .06       0  129.67     .12       0   354.1    .045       0
   373.7     .12       0
Bank Sta=354.1,373.7
XS Rating Curve= 0 ,0
Exp/Cntr=0.3,0.1

Type RM Length L Ch R = 1 ,22281.7 ,252.7,238.8,210.8
XS GIS Cut Line= 3
      2081020.77      258670.341     2081061.649       259020.17
     2081240.939      259419.988
#Sta/Elev= 30
       0 2197.91   28.862195.486    65.2 2193.46   114.1 2193.31   120.7  2192.5
   127.2 2190.54   146.8  2187.7   192.4 2182.27   234.8 2178.18   244.6 2176.01
   254.4 2168.76   264.2 2164.86   277.2  2161.8   283.7 2159.07     300 2154.31
   306.6 2152.68   319.6 2154.18   329.4 2155.46     349  2156.2   365.3 2158.75
     398 2166.91   414.3 2173.78   430.7 2177.71   486.3 2188.08   535.3 2195.23
   581.1 2198.65   643.2 2201.99   698.8 2203.01   764.2 2201.55   790.4 2199.42
#Mann= 4 ,-1 , 0
       0     .06       0   28.86     .12       0     300    .045       0
   319.6     .12       0
Bank Sta=300,319.6
XS Rating Curve= 0 ,0
Exp/Cntr=0.3,0.1

Type RM Length L Ch R = 1 ,22042.8 ,161,196,186.6
XS GIS Cut Line= 3
     2080841.566      258804.915     2080851.263      259102.283
     2081206.812      259422.277
#Sta/Elev= 30
       0 2194.85    2.572195.177      49 2196.48   84.362195.269   147.1 2190.72
   173.3 2185.58   189.6 2180.71   225.6 2173.09   241.9 2167.56   258.3 2159.36
   277.9 2153.11     291 2150.44   307.4 2150.28   317.2 2148.89   330.3 2148.03
   336.8 2148.87   353.2 2152.91     363 2157.48   372.9 2163.37   379.4 2165.46
   415.5 2171.81     445  2175.9   474.4 2181.97   497.4 2185.03   553.1 2189.92
   641.5  2195.3     671 2195.34   697.2 2196.43   720.2 2195.84   775.9 2196.45
#Mann= 5 ,-1 , 0
       0     .12       0    2.57     .06       0   84.36     .12       0
   317.2    .045       0   336.8     .12       0
Bank Sta=317.2,336.8
XS Rating Curve= 0 ,0
Exp/Cntr=0.3,0.1

Type RM Length L Ch R = 1 ,21846.8 ,301.9,303,356.3
XS GIS Cut Line= 3
     2080812.476      258827.541     2080740.521      259266.808
      2081090.45      259448.135
#Sta/Elev= 30
       0 2196.53    55.6 2197.22   95.472195.248   153.8 2189.24   176.7 2188.81
   242.2 2181.56   274.9 2176.27   304.4 2168.51   340.4 2168.81   343.7 2168.44
   353.5 2165.15   382.9 2159.96   412.4 2157.28   428.8 2154.74   445.1  2154.9
   458.2  2146.9   466.4 2143.69   477.7 2142.68   487.5 2143.63   526.6 2149.72
   546.1 2155.22   575.4 2160.06   591.7 2161.81   614.5 2165.87     634 2167.41
   666.6 2173.05   682.9 2174.01   754.6 2181.06   803.4 2181.55   839.2 2179.21
#Mann= 4 ,-1 , 0
       0     .06       0   95.47     .12       0   466.4    .045       0
   487.5     .12       0
Bank Sta=466.4,487.5
XS Rating Curve= 0 ,0
Exp/Cntr=0.3,0.1

Type RM Length L Ch R = 1 ,21543.8 ,258.5,268.3,274.2
XS GIS Cut Line= 3
     2080799.547      258824.309      2080689.65      259393.187
     2080644.398      259541.871
#Sta/Elev= 30
       0 2196.36    49.1 2197.89    85.1 2196.71  112.442194.627   134.2 2192.46
   176.8 2190.67   245.5 2183.81   297.9 2175.01   333.9 2174.78   360.1 2173.48
   369.9 2172.13   399.4 2171.98   422.3  2170.6   441.9 2167.48   474.6 2167.28
   517.2 2163.69   530.3 2161.17   546.7 2154.84   559.8 2148.52   585.9 2141.39
   598.8 2140.06     628 2139.44   637.7 2136.94   640.9 2137.01   647.8 2139.64
   666.8 2152.47   673.3  2154.8     696 2159.02   712.2 2158.25   734.8 2150.02
#Mann= 4 ,-1 , 0
       0     .06       0  112.44     .12       0     628    .045       0
   647.8     .12       0
Bank Sta=628,647.8
XS Rating Curve= 0 ,0
Exp/Cntr=0.3,0.1

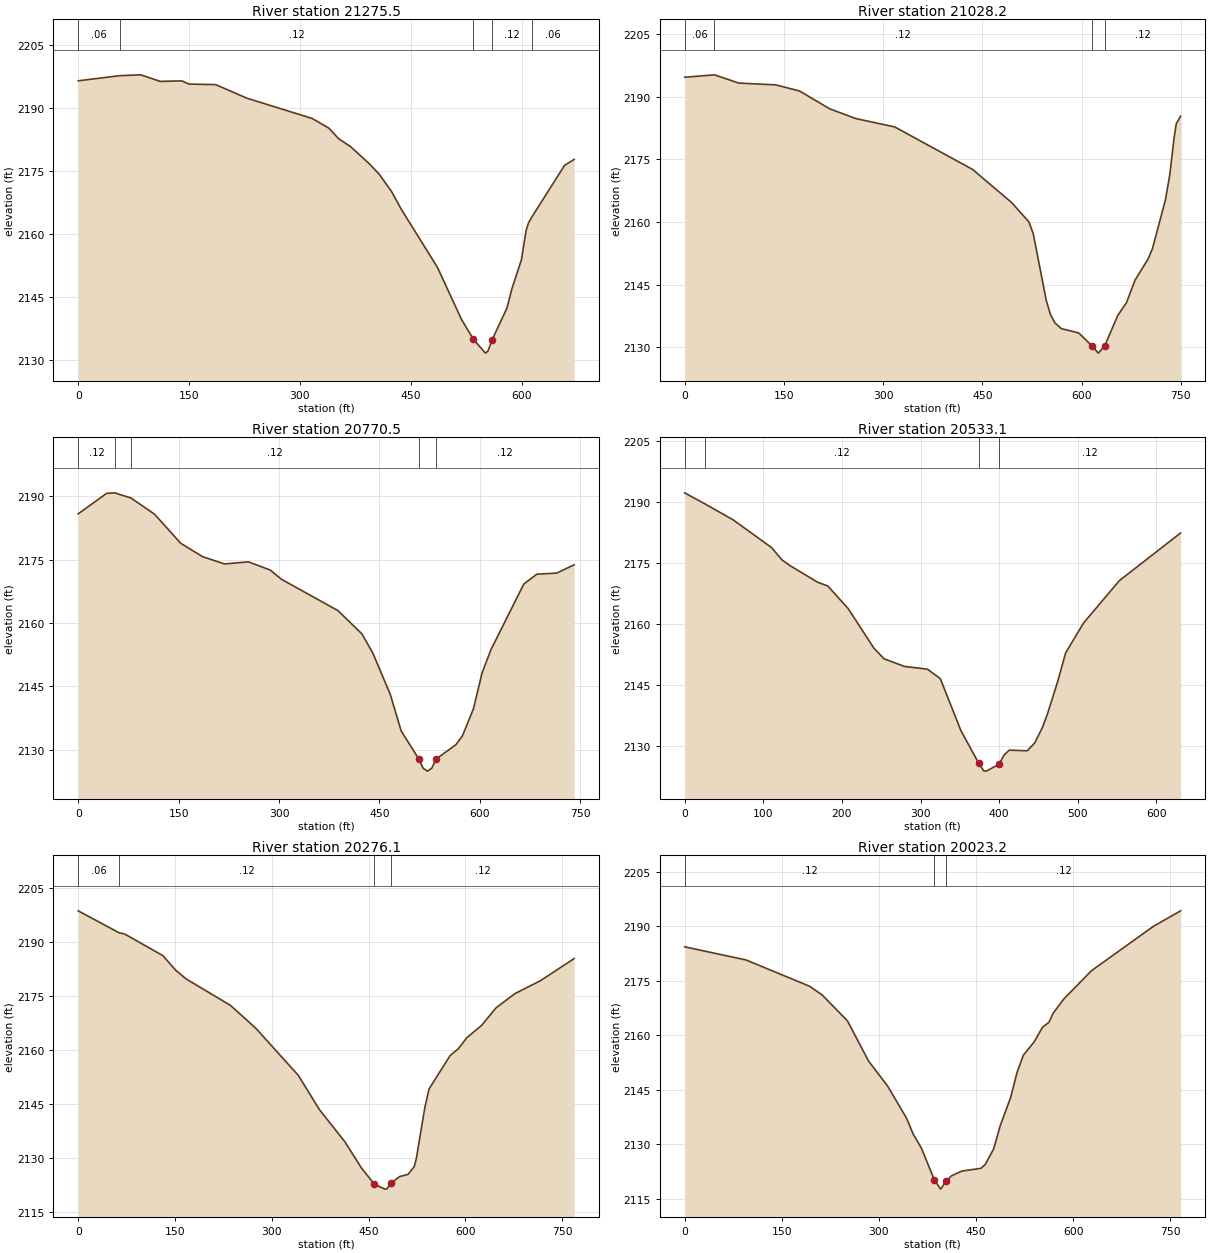
Type RM Length L Ch R = 1 ,21275.5 ,224.2,247.3,268.5
XS GIS Cut Line= 3
     2080770.456      258821.077      2080489.25      259260.664
     2080414.907      259389.955
#Sta/Elev= 30
       0  2196.4   55.962197.617    84.8 2197.82   110.9 2196.26   140.2 2196.38
     150 2195.62   185.9  2195.5   228.3 2192.27   316.4 2187.47   339.2 2185.16
   352.2 2182.68   368.6 2180.76   394.6 2176.58   407.7 2174.13     424  2170.1
     437 2165.93     486 2152.12   518.6 2139.74   534.8    2135     551 2131.74
   554.3 2132.21     560  2134.9   580.2 2142.49   586.7 2146.98   599.6 2153.88
   606.1 2160.92   609.4 2162.73   614.32164.208     658 2176.32     671 2177.74
#Mann= 5 ,-1 , 0
       0     .06       0   55.96     .12       0   534.8    .045       0
     560     .12       0   614.3     .06       0
Bank Sta=534.8,560
XS Rating Curve= 0 ,0
Exp/Cntr=0.3,0.1

Type RM Length L Ch R = 1 ,21028.2 ,228,257.8,282.7
XS GIS Cut Line= 3
     2080754.295      258801.683     2080298.546         259154.
      2080146.63      259238.038
#Sta/Elev= 30
       0 2194.67      452195.245    81.8 2193.27   137.5 2192.84   173.5 2191.39
   219.3  2187.1   258.6 2184.78   317.5 2182.77   435.3 2172.59   494.2 2164.68
   520.4 2160.03     527 2157.15   546.6 2141.24   553.1 2137.79   559.7 2135.85
   569.5 2134.48   595.7 2133.45   615.4 2130.41   625.2 2128.62     635 2130.38
   654.7 2137.64   667.8 2140.68   680.9 2146.12   700.5 2151.14   707.1 2153.62
   726.7 2165.27   733.3  2171.3   739.8 2180.09   743.1  2183.5   749.7 2185.34
#Mann= 4 ,-1 , 0
       0     .06       0      45     .12       0   615.4    .045       0
     635     .12       0
Bank Sta=615.4,635
XS Rating Curve= 0 ,0
Exp/Cntr=0.3,0.1

Type RM Length L Ch R = 1 ,20770.5 ,236.2,237.4,236.8
XS GIS Cut Line= 3
     2080757.527      258737.038     2080321.172      258950.367
     2080069.055       258911.58
#Sta/Elev= 30
       0 2185.83    42.4 2190.67    54.32190.805   78.722189.592   114.1 2185.74
   153.2 2178.85   185.8 2175.69   218.4 2173.97   254.3 2174.46   286.9 2172.52
   303.2 2170.38   387.9 2162.93   423.8 2157.41   440.1 2152.86   466.2 2143.07
   482.4 2134.44   508.6 2127.83   515.1 2125.64   521.7 2124.92   528.2 2125.63
   534.8 2127.81   564.2 2131.18     574 2133.29   590.4  2139.7   603.4 2148.24
   616.5 2153.65   665.6 2169.22   685.2 2171.55   714.6  2171.8   740.8 2173.76
#Mann= 5 ,-1 , 0
       0     .12       0    54.3     .06       0   78.72     .12       0
   508.6    .045       0   534.8     .12       0
Bank Sta=508.6,534.8
XS Rating Curve= 0 ,0
Exp/Cntr=0.3,0.1

Type RM Length L Ch R = 1 ,20533.1 ,254.8,257,257.1
XS GIS Cut Line= 3
     2080738.134      258656.231      2080418.14      258743.502
     2080124.004      258688.554
#Sta/Elev= 30
       0 2192.26   25.922189.515    61.8 2185.59   110.6 2178.77   123.6 2175.77
   133.3 2174.41   169.1 2170.24   182.1 2169.31   208.1 2163.72   240.6 2154.03
   253.6 2151.38   279.6  2149.5   308.9 2148.82   325.2 2146.49   351.2 2133.78
     374 2125.67   380.5 2123.75   383.7 2123.71     400 2125.42   406.5 2127.73
     413 2128.88   435.8 2128.72   445.5 2130.71   455.3 2134.56   461.8 2137.95
   474.8 2145.97   484.6 2152.81   507.3 2160.16   552.8  2170.6   630.9 2182.38
#Mann= 4 ,-1 , 0
       0     .06       0   25.92     .12       0     374    .045       0
     400     .12       0
Bank Sta=374,400
XS Rating Curve= 0 ,0
Exp/Cntr=0.3,0.1

Type RM Length L Ch R = 1 ,20276.1 ,250.6,252.9,243.1
XS GIS Cut Line= 3
     2080885.121      258481.076     2080472.439      258501.271
     2080126.426      258420.592
#Sta/Elev= 30
       0 2198.68   63.352192.585    72.1 2192.23   131.2 2186.24   150.8 2182.22
   167.2 2179.77   236.1 2172.39   275.4 2166.02     341 2152.98   373.8 2143.45
   413.2 2134.52   439.2 2127.16   458.8 2122.76   475.1 2121.36   478.4 2121.46
   484.9 2123.08   497.9 2124.84     511 2125.45   520.7 2127.62     524 2129.88
     537  2143.9   543.6 2149.17   576.2 2158.44   589.2 2160.41   602.2 2163.44
     625 2166.84   647.9 2171.81   677.2 2175.73   716.3 2179.27   768.5 2185.42
#Mann= 4 ,-1 , 0
       0     .06       0   63.35     .12       0   458.8    .045       0
   484.9     .12       0
Bank Sta=458.8,484.9
XS Rating Curve= 0 ,0
Exp/Cntr=0.3,0.1

Type RM Length L Ch R = 1 ,20023.2 ,248.2,244.4,236.8
XS GIS Cut Line= 3
     2080831.514      258094.949     2080527.248      258279.478
     2080118.844      258314.933
#Sta/Elev= 30
       0 2184.34    94.7 2180.72   192.6  2173.5   212.2  2171.1   251.4 2163.93
     284 2152.85   313.4 2145.98   342.8 2137.07   352.6 2132.85   365.7 2128.83
   385.4 2120.19   395.2 2117.59   404.2 2119.82   411.6 2121.22     428 2122.56
   457.5 2123.33   464.1 2124.37   477.2 2128.72     487 2134.91   503.4 2142.88
   513.3 2149.78   523.1 2154.52   539.5 2158.11   552.6 2162.19   562.5 2163.54
     569 2166.04   585.4 2169.96     628 2177.73   723.2 2189.91   765.8 2194.25
#Mann= 3 ,-1 , 0
       0     .12       0   385.4    .045       0   404.2     .12       0
Bank Sta=385.4,404.2
XS Rating Curve= 0 ,0
Exp/Cntr=0.3,0.1

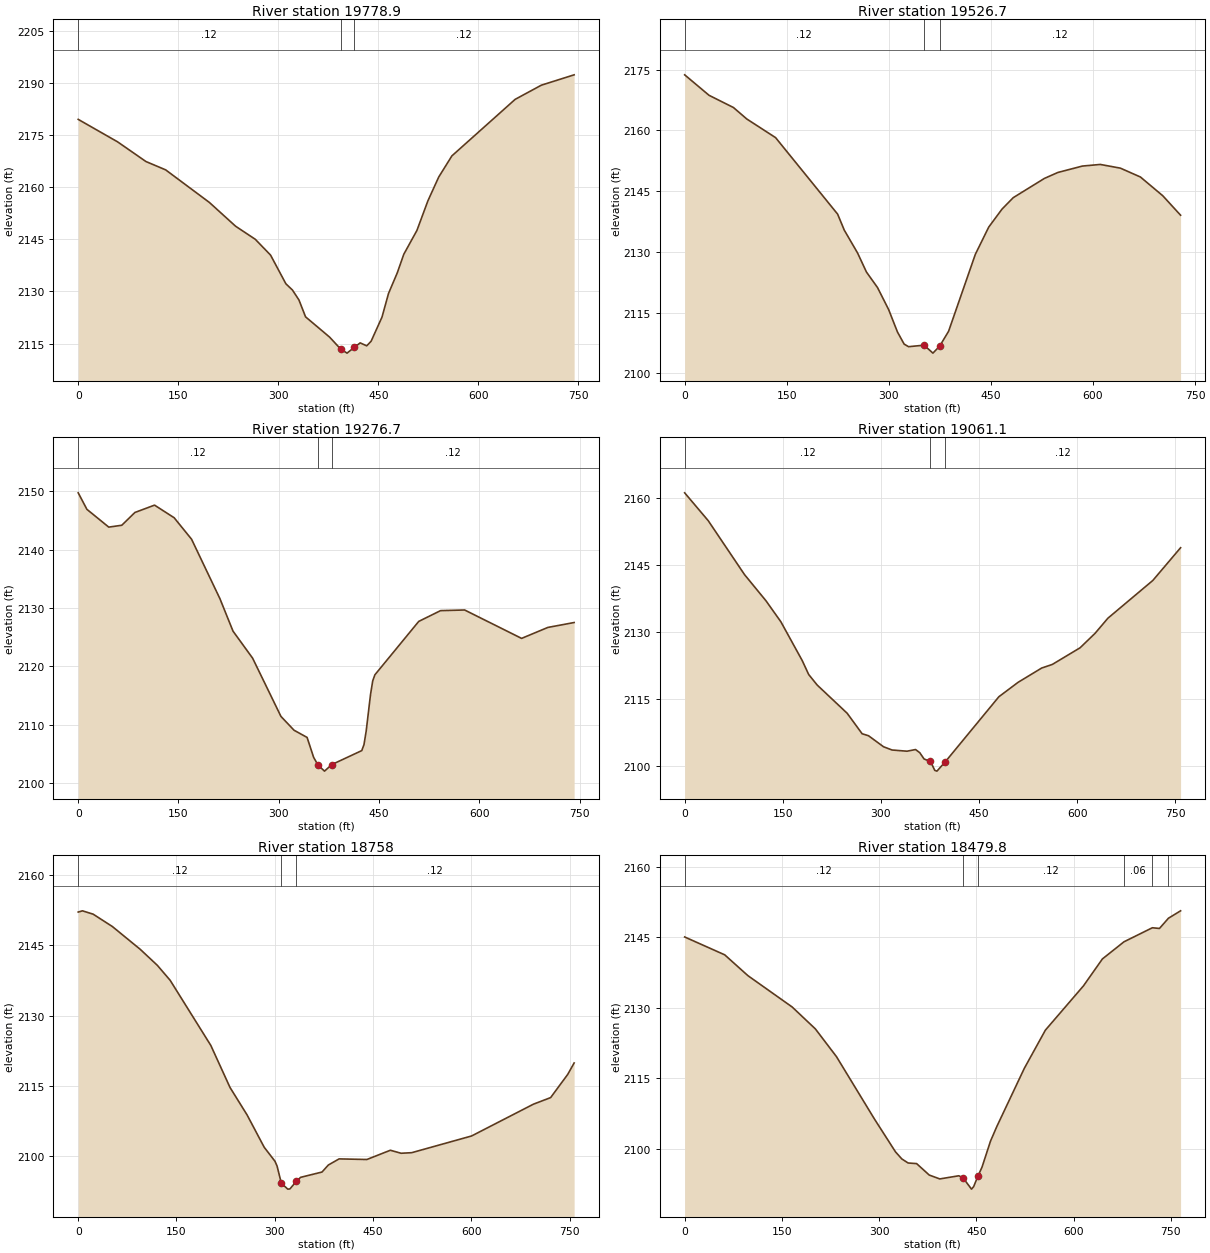
Type RM Length L Ch R = 1 ,19778.9 ,234.7,252.2,269.3
XS GIS Cut Line= 3
     2080787.242      258012.628     2080410.489       258063.85
     2080054.849      258138.493
#Sta/Elev= 30
       0 2179.56      59 2173.09   101.6 2167.41   131.1 2165.02   196.7 2155.63
     236 2148.78   265.5 2145.02   288.4 2140.47   311.4  2132.2   321.2 2130.41
     331 2127.54   340.9 2122.68   376.9 2116.85   393.3 2113.44   403.1 2112.23
   413.8 2113.86   422.8 2115.18   432.6 2114.33   439.2 2115.66   455.5  2122.6
   465.3 2129.42   478.4 2135.35   488.2 2140.71   507.9 2147.58   524.3 2156.08
   540.6 2162.96   560.3 2169.04   655.2 2185.33   694.5 2189.41   743.6 2192.39
#Mann= 3 ,-1 , 0
       0     .12       0   393.3    .045       0   413.8     .12       0
Bank Sta=393.3,413.8
XS Rating Curve= 0 ,0
Exp/Cntr=0.3,0.1

Type RM Length L Ch R = 1 ,19526.7 ,260,250,233.4
XS GIS Cut Line= 3
     2080775.415      257915.876      2080419.89      257834.014
     2080066.901      257745.764
#Sta/Elev= 30
       0 2173.69    35.8 2168.64    71.7 2165.62    91.2  2162.8   133.6 2158.19
   224.8  2139.3   234.5 2135.37   254.1 2129.71   267.1 2125.02   283.4 2121.18
   299.7 2115.76   312.7 2110.21   322.5 2107.23     329 2106.59   351.8 2106.96
   364.8    2105   374.7 2106.73   387.8 2110.39   427.1 2129.38   446.8 2136.11
   466.4 2140.56   482.8 2143.37   528.7 2148.13   548.4 2149.59   584.4 2151.17
   610.7 2151.57   640.2 2150.66   669.7 2148.47   702.5 2143.85   728.7 2139.04
#Mann= 3 ,-1 , 0
       0     .12       0   351.8    .045       0   374.7     .12       0
Bank Sta=351.8,374.7
XS Rating Curve= 0 ,0
Exp/Cntr=0.3,0.1

Type RM Length L Ch R = 1 ,19276.7 ,213.3,215.6,212.5
XS GIS Cut Line= 3
     2080827.869      257554.902     2080458.693      257599.001
     2080089.095      257617.602
#Sta/Elev= 30
       0 2149.76      13 2146.93    45.7 2143.88    65.2  2144.2    84.8 2146.39
   114.2 2147.65   143.5 2145.49   169.6  2141.8     212 2131.61   231.6 2126.04
   260.9 2121.41   303.3 2111.42   322.9 2109.05   342.4 2107.82   352.2  2104.4
   358.8 2103.06   368.5 2102.04   379.3 2103.16   424.2 2105.56   427.5 2106.58
   430.8  2108.9   437.3 2115.18   440.6 2117.52   443.8 2118.55   509.4 2127.71
   542.1 2129.56   578.1 2129.67   663.3  2124.8   702.6 2126.68   741.9 2127.52
#Mann= 3 ,-1 , 0
       0     .12       0   358.8    .045       0   379.3     .12       0
Bank Sta=358.8,379.3
XS Rating Curve= 0 ,0
Exp/Cntr=0.3,0.1

Type RM Length L Ch R = 1 ,19061.1 ,313.4,303.1,290.1
XS GIS Cut Line= 2
     2080822.172      257379.488      2080065.72      257431.553
#Sta/Elev= 30
       0 2161.23      36    2155    91.5 2142.93   124.2 2137.09   147.1 2132.37
   179.8 2123.67   189.6 2120.57   202.6 2118.21   248.4  2111.9   271.3 2107.31
   281.1 2106.86     304  2104.4     317 2103.67   339.9  2103.4     353 2103.77
   359.5 2103.06     366 2101.66   375.8  2101.1   382.4 2099.11   385.7 2098.94
   398.7 2101.07   480.4 2115.59   509.8 2118.82   545.8 2122.01   562.1 2122.82
   604.6 2126.55   627.5 2129.79   647.1 2133.17   715.8 2141.62   758.2 2148.94
#Mann= 3 ,-1 , 0
       0     .12       0   375.8    .045       0   398.7     .12       0
Bank Sta=375.8,398.7
XS Rating Curve= 0 ,0
Exp/Cntr=0.3,0.1

Type RM Length L Ch R = 1 ,18758   ,292.8,278.2,276.9
XS GIS Cut Line= 3
     2080796.314      257033.636     2080408.443      257188.784
     2080072.948      257238.279
#Sta/Elev= 30
       0 2152.04     6.5  2152.3    22.8 2151.59    52.2 2148.95    94.6 2144.11
   120.8 2140.69   140.3 2137.51   202.4 2123.63   231.7 2114.68   257.8 2108.82
   283.9 2101.94   300.3 2098.97   303.5 2097.95     310  2094.3   319.8 2093.03
   323.1 2093.07   332.9 2094.69   339.4 2095.54   372.1 2096.67   381.8 2098.17
   398.2 2099.47   440.6 2099.34   476.4 2101.31   492.8 2100.67     509 2100.79
   600.4 2104.35   694.9 2111.13     721 2112.52   747.1 2117.46   756.9  2119.9
#Mann= 3 ,-1 , 0
       0     .12       0     310    .045       0   332.9     .12       0
Bank Sta=310,332.9
XS Rating Curve= 0 ,0
Exp/Cntr=0.3,0.1

Type RM Length L Ch R = 1 ,18479.8 ,164,268.2,160.1
XS GIS Cut Line= 3
      2080768.95      256952.123     2080440.766      256936.668
     2080017.339      257043.333
#Sta/Elev= 30
       0 2145.07    61.8 2141.27    97.6 2136.84   165.9 2130.17   201.7 2125.51
   234.2 2119.62   292.8 2106.35   325.3 2099.36   335.1 2097.85   344.8 2096.99
   357.9 2096.86   377.4 2094.42   393.7  2093.6     423 2094.27   429.6 2093.82
   442.6 2091.43   445.9 2091.96   452.4 2094.15   458.9 2096.14   471.9 2101.64
   481.7 2104.76   524.1 2117.13   556.6 2125.25   615.3 2134.66   644.6  2140.4
  677.872144.041  721.642147.028   732.6 2146.88  746.492149.057   765.2 2150.63
#Mann= 6 ,-1 , 0
       0     .12       0   429.6    .045       0   452.4     .12       0
  677.87     .06       0  721.64    .016       0  746.49     .06       0
Bank Sta=429.6,452.4
XS Rating Curve= 0 ,0
Exp/Cntr=0.3,0.1