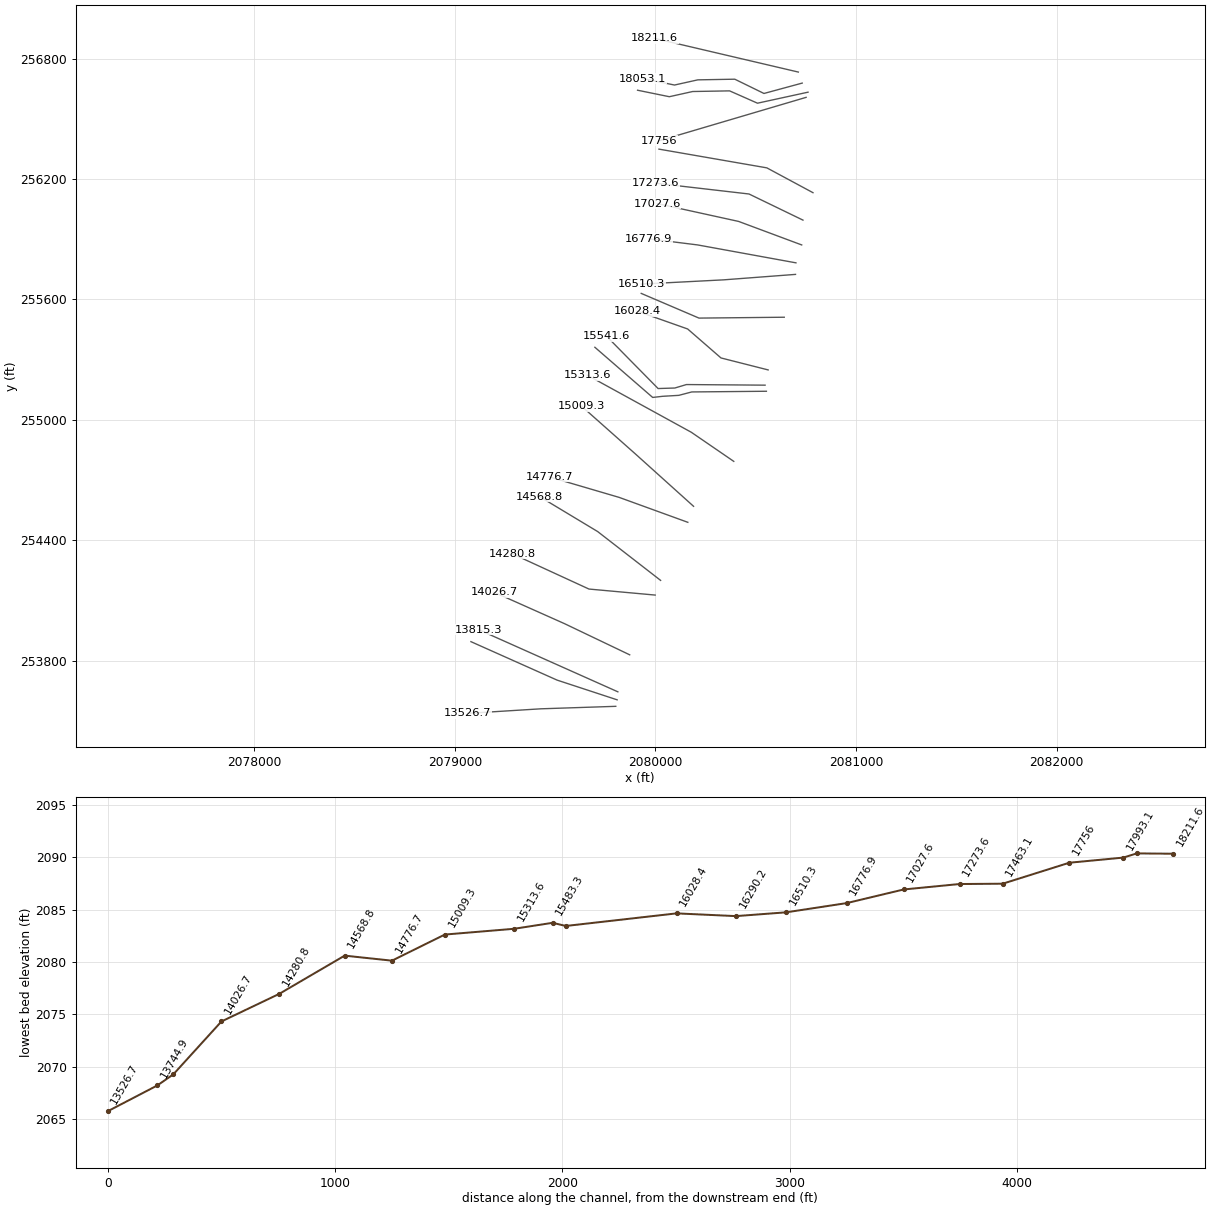
HEC-RAS study LAURELCK4.prj: LAURELCK4

--- LAURELCK4.g01 (geometry) --- (continued)

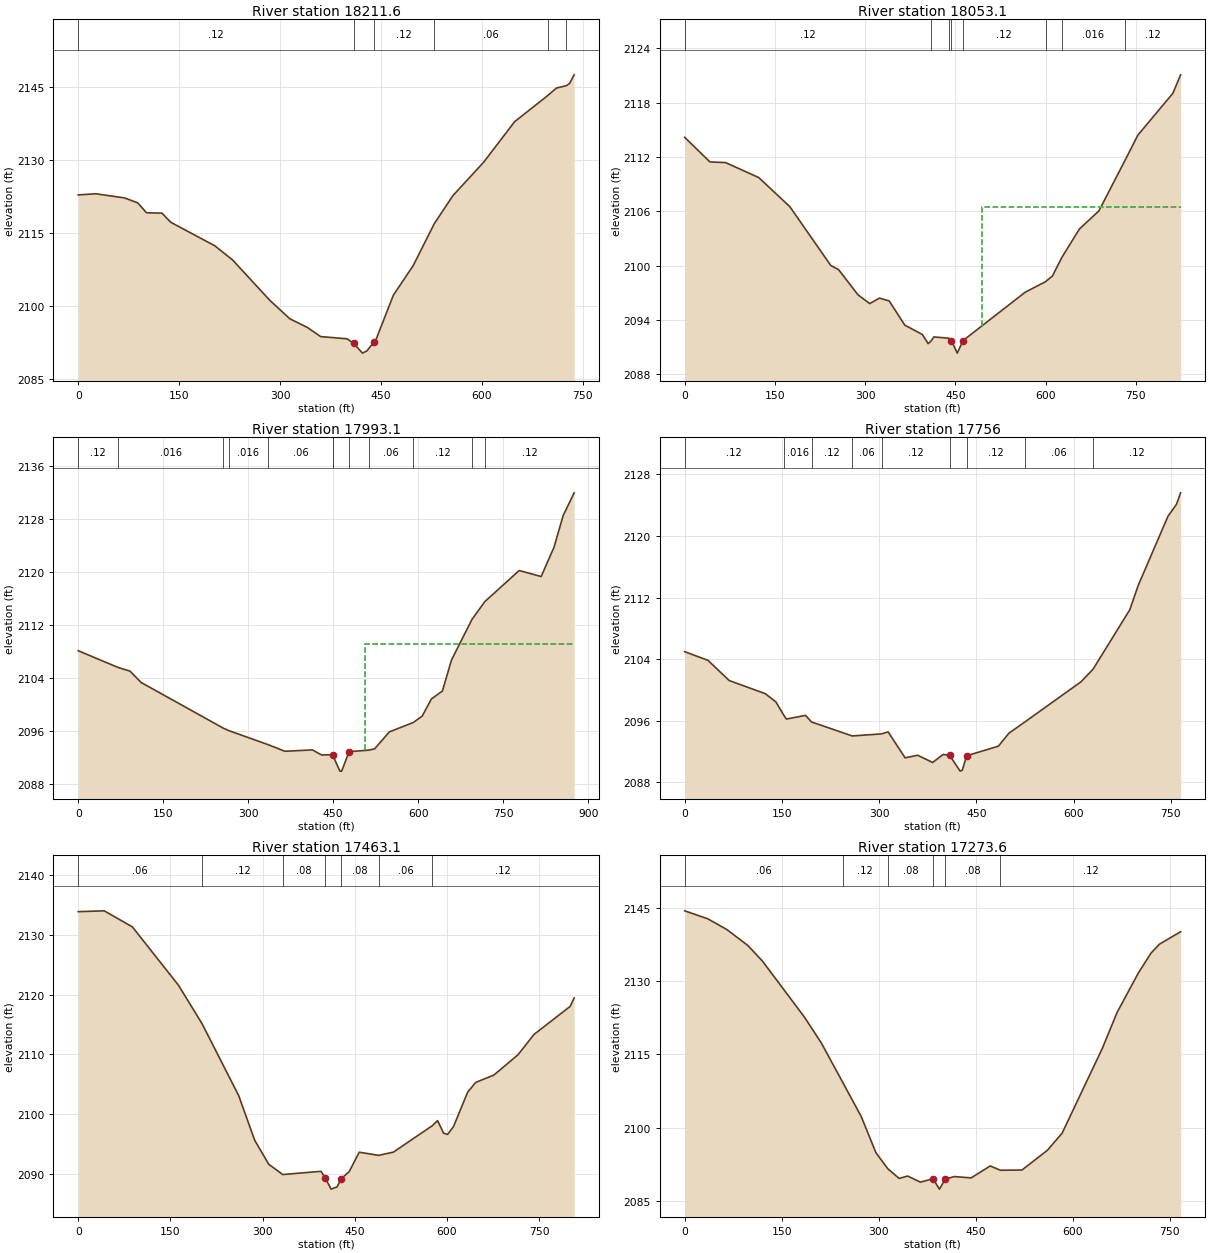
Type RM Length L Ch R = 1 ,18211.6 ,162.7,158.4,164.4
XS GIS Cut Line= 2
     2080712.276      256733.035     2079994.713      256901.113
#Sta/Elev= 30
       0 2122.86    26.2  2123.1    68.8 2122.24    88.4 2121.24   101.5 2119.19
   124.5 2119.11   137.6 2117.23   203.1 2112.39   229.3  2109.5     285 2101.15
   314.4 2097.39   340.6  2095.6   360.3 2093.72   399.6 2093.27   409.4 2092.31
   422.5 2090.32   429.1 2090.79   438.9 2092.51   442.2 2092.99   468.4 2102.25
   497.9 2108.34   529.12116.933   556.8 2122.71   602.7 2129.62   648.6 2137.93
  697.85 2143.31   710.8 2144.85  725.442145.324   730.4 2145.83     737 2147.56
#Mann= 6 ,-1 , 0
       0     .12       0   409.4    .045       0   438.9     .12       0
   529.1     .06       0  697.85    .016       0  725.44     .08       0
Bank Sta=409.4,438.9
XS Rating Curve= 0 ,0
Exp/Cntr=0.3,0.1

Type RM Length L Ch R = 1 ,18053.1 ,77.4,60,62.8
XS GIS Cut Line= 6
     2080731.669      256678.087     2080540.966      256626.371
     2080395.514      256697.481     2080211.275      256694.248
     2080094.914       256668.39     2079936.533      256700.713
#Sta/Elev= 30
       0 2114.18    42.1 2111.46      68 2111.39   123.1 2109.74   174.9 2106.52
   242.9 2100.03   255.9 2099.57   288.3 2096.78   307.7 2095.82   323.9 2096.43
   340.1 2096.11     366 2093.44   395.1 2092.41   404.8  2091.4  409.262091.658
   414.4 2092.14  439.412091.997   443.6 2091.73   453.2 2090.35   462.9 2091.74
   566.3 2097.08  599.972098.238   611.4 2098.86  627.172100.924   656.5 2104.07
   688.8 2106.06   732.22111.644   753.5 2114.42   811.7 2119.04   824.6 2121.08
#Mann= 8 ,-1 , 0
       0     .12       0  409.26     .06       0  439.41     .12       0
   443.6    .045       0   462.9     .12       0  599.97     .06       0
  627.17    .016       0   732.2     .12       0
#XS Ineff= 2 , 0
                          494.33         2106.47
Permanent Ineff=
       F       F
Bank Sta=443.6,462.9
XS Rating Curve= 0 ,0
Exp/Cntr=0.3,0.1

Type RM Length L Ch R = 1 ,17993.1 ,169.3,237.1,184.1
XS GIS Cut Line= 6
      2080760.76      256632.835     2080508.643      256577.887
     2080369.656        256639.3     2080185.417      256636.068
     2080069.055      256610.209     2079910.675      256642.532
#Sta/Elev= 30
       0 2108.15   70.452105.615    91.5 2105.06     111 2103.35  255.852096.452
  265.562096.077  335.082093.953   364.7 2092.95   413.2 2093.16   429.4 2092.39
  448.78 2092.43   448.8 2092.43   461.7 2089.95   464.9 2089.95   477.9 2092.89
  512.392093.117   523.1 2093.32     549 2095.88  591.24  2097.3   607.1 2098.28
   623.2 2100.86   642.6 2102.05   658.7 2106.75  694.742112.872  717.552115.574
   778.1 2120.27   816.9 2119.36   839.5 2123.77   855.7 2128.56   875.1 2132.01
#Mann= 12 ,-1 , 0
       0     .12       0   70.45    .016       0  255.85     .12       0
  265.56    .016       0  335.08     .06       0  448.78     .12       0
   448.8    .045       0   477.9     .12       0  512.39     .06       0
  591.24     .12       0  694.74     .06       0  717.55     .12       0
#XS Ineff= 2 , 0
                          505.67         2109.16
Permanent Ineff=
       F       F
Bank Sta=448.8,477.9
XS Rating Curve= 0 ,0
Exp/Cntr=0.3,0.1

Type RM Length L Ch R = 1 ,17756   ,280.2,292.9,259.2
XS GIS Cut Line= 2
     2080751.063      256606.977     2080017.339      256390.416
#Sta/Elev= 30
       0 2104.97      36 2103.84    68.7 2101.22   124.2 2099.52   140.6 2098.46
  152.512096.776   156.9 2096.22   186.4  2096.7  195.692095.842  258.472094.028
  303.712094.294   313.8 2094.56     340 2091.19   359.6 2091.52   382.5 2090.58
   398.8 2091.63   408.7  2091.5     425 2089.46   428.3 2089.59   434.8 2091.45
   483.9  2092.7   500.2 2094.39  524.532095.827   611.4 2101.06   629.9 2102.69
   686.6 2110.41   699.6 2113.57   745.4 2122.53   758.5 2124.09     765 2125.59
#Mann= 9 ,-1 , 0
       0     .12       0  152.51    .016       0  195.69     .12       0
  258.47     .06       0  303.71     .12       0   408.7    .045       0
   434.8     .12       0  524.53     .06       0   629.9     .12       0
Bank Sta=408.7,434.8
XS Rating Curve= 0 ,0
Exp/Cntr=0.3,0.1

Type RM Length L Ch R = 1 ,17463.1 ,244.9,189.5,175.1
XS GIS Cut Line= 3
     2080785.334      256131.933       2080555.3      256255.631
       2080017.3      256348.966
#Sta/Elev= 30
       0 2133.89    42.4 2134.03    88.2 2131.34   163.2 2121.58  201.472115.163
   261.2 2103.11   287.3 2095.63   310.2 2091.61  332.97  2089.9   395.2 2090.44
   401.8 2089.37   411.6 2087.46   421.4 2087.84   427.9  2089.2     441 2090.38
   457.4 2093.64  488.942093.111     513 2093.65  576.382098.076   584.9 2098.93
   594.7 2096.83   601.2 2096.61     611 2097.96   633.9 2103.69     647 2105.32
   676.4 2106.54   715.7 2109.93   741.8 2113.34   800.7 2118.04   807.2 2119.46
#Mann= 7 ,-1 , 0
       0     .06       0  201.47     .12       0  332.97     .08       0
   401.8    .045       0   427.9     .08       0  488.94     .06       0
  576.38     .12       0
Bank Sta=401.8,427.9
XS Rating Curve= 0 ,0
Exp/Cntr=0.3,0.1

Type RM Length L Ch R = 1 ,17273.6 ,174.1,246,171.1
XS GIS Cut Line= 3
     2080735.421      255995.215     2080466.324      256125.423
     2080001.703      256179.106
#Sta/Elev= 30
       0 2144.38    35.7 2142.75      65 2140.57    97.5 2137.31   120.2  2134.1
   185.2 2122.62   211.2 2117.35  244.182109.322     273 2102.27   295.7 2094.87
  314.242091.567   331.6 2089.62   344.7 2090.11   364.4 2088.86     384 2089.55
   393.8 2087.43   402.8 2089.46   416.7    2090   442.9 2089.73   472.3 2092.17
   488.22091.292   521.4 2091.34   560.6 2095.36   583.5 2098.88   645.6 2116.21
   668.5 2123.59   701.2 2131.62   720.9 2135.72     734 2137.56   766.7  2140.1
#Mann= 6 ,-1 , 0
       0     .06       0  244.18     .12       0  314.24     .08       0
     384    .045       0   402.8     .08       0   488.2     .12       0
Bank Sta=384,402.8
XS Rating Curve= 0 ,0
Exp/Cntr=0.3,0.1

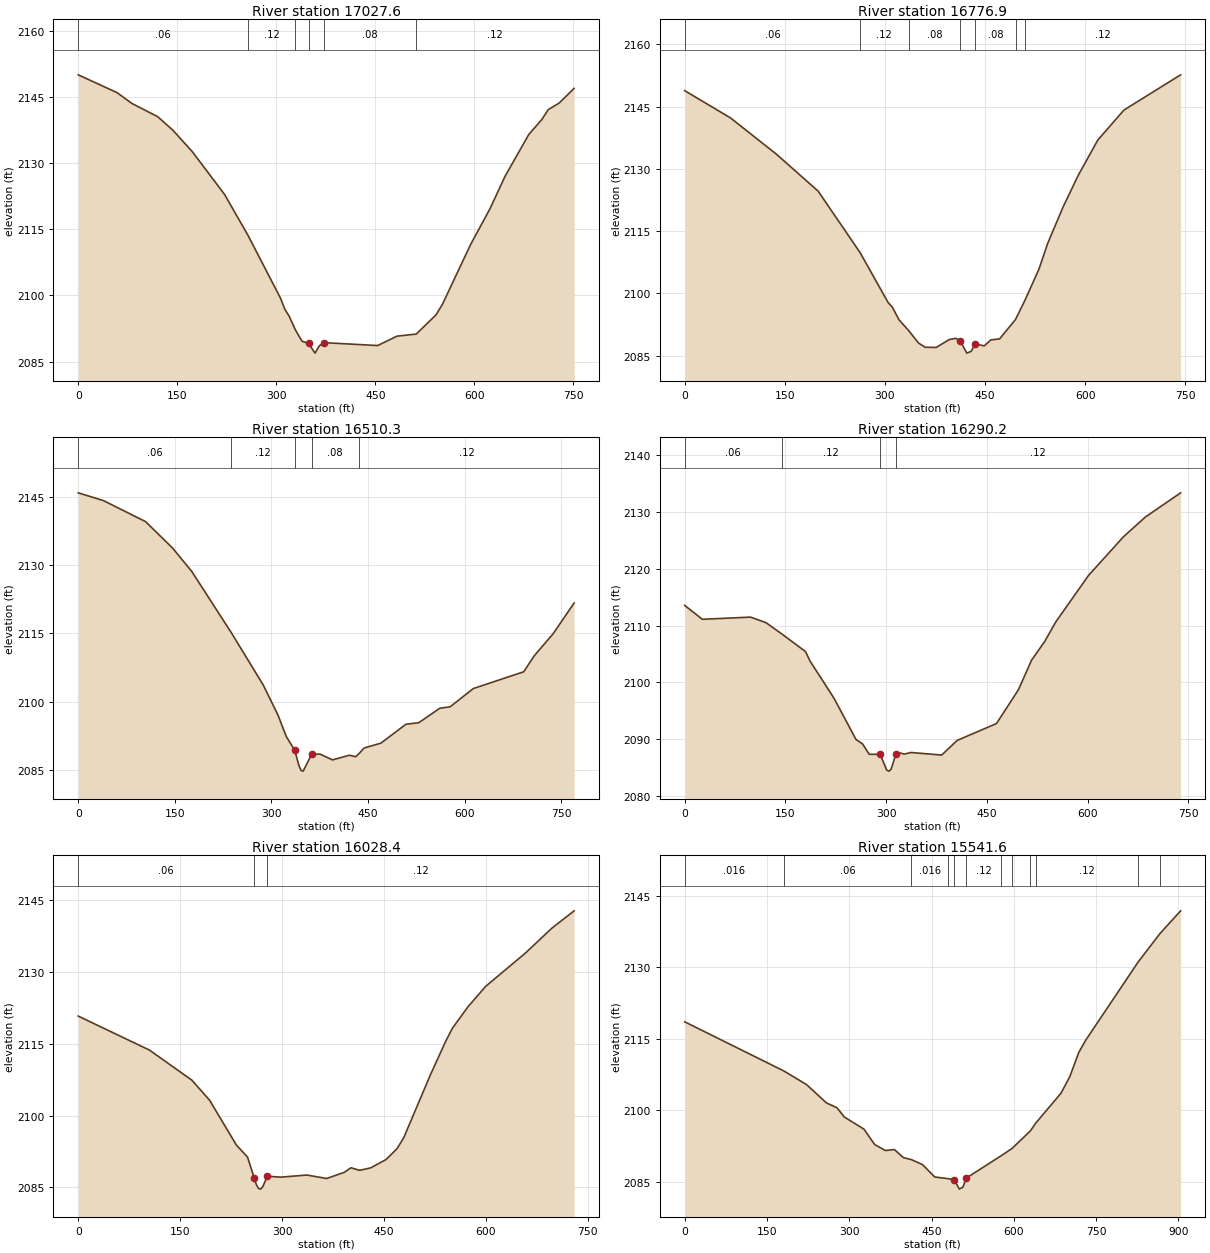
Type RM Length L Ch R = 1 ,17027.6 ,188.8,250.7,215.3
XS GIS Cut Line= 3
     2080729.106      255871.536     2080414.435      255988.723
     2080008.619      256077.699
#Sta/Elev= 30
       0 2150.08    58.7 2146.05    81.5 2143.57   120.6 2140.56   143.4 2137.51
   172.8 2132.64   221.7 2122.93  257.132113.656   306.4 2099.39     313 2096.86
   319.5 2095.31  329.082092.163     339 2089.61   348.9 2089.12   358.7 2086.91
   365.2 2088.56   371.8 2089.29   453.6 2088.63     483 2090.77  512.022091.233
   541.9 2095.58   551.7 2097.99   594.2 2111.52   623.7 2119.68   646.6 2127.06
   682.5 2136.54   702.2 2139.93     712 2142.19   728.3 2143.65   751.2 2147.01
#Mann= 6 ,-1 , 0
       0     .06       0  257.13     .12       0  329.08     .08       0
   348.9    .045       0   371.8     .08       0  512.02     .12       0
Bank Sta=348.9,371.8
XS Rating Curve= 0 ,0
Exp/Cntr=0.3,0.1

Type RM Length L Ch R = 1 ,16776.9 ,175.2,266.6,204.1
XS GIS Cut Line= 3
      2080700.45      255782.317     2080210.442      255871.536
     2079967.387      255901.918
#Sta/Elev= 30
       0 2148.87    68.8 2142.28   137.6 2133.53   199.9 2124.66  262.882109.818
   304.7 2097.83   311.3 2096.63   321.1 2093.65  335.422091.074   350.6 2088.01
   360.4 2087.02   376.8 2086.98   396.5 2088.89   406.3 2089.17   412.9 2088.55
   422.7 2085.61   429.2 2086.04   435.3 2087.82   448.9 2087.36   458.7  2088.8
   471.8 2089.04  495.712093.729  510.182098.478   530.7 2105.82   543.8 2112.03
   566.6 2120.72   589.5 2128.42   618.9 2136.95   658.1 2144.19     743 2152.68
#Mann= 7 ,-1 , 0
       0     .06       0  262.88     .12       0  335.42     .08       0
   412.9    .045       0   435.3     .08       0  495.71     .06       0
  510.18     .12       0
Bank Sta=412.9,435.3
XS Rating Curve= 0 ,0
Exp/Cntr=0.3,0.1

Type RM Length L Ch R = 1 ,16510.3 ,212.7,220.2,204.6
XS GIS Cut Line= 3
     2080698.248      255724.751     2080340.127      255697.584
     2079929.518       255676.39
#Sta/Elev= 30
       0 2145.93    39.2 2144.22   104.5 2139.61   146.9 2133.74   176.3 2128.66
   237.9 2115.15   287.3 2103.69   310.2 2097.09   323.2 2092.33   336.3 2089.32
   342.8 2085.97   346.1 2084.88   349.4 2084.73   362.4 2088.41   375.5 2088.48
     395  2087.2   421.2 2088.23   430.9  2087.9  436.17 2088.58     444 2089.81
   470.1 2090.88   509.2 2095.05   528.8 2095.36   561.5 2098.55   577.8 2098.88
   613.7 2102.89     692 2106.58   708.3 2110.09   737.7 2114.95   770.3 2121.71
#Mann= 5 ,-1 , 0
       0     .06       0   237.9     .12       0   336.3    .045       0
   362.4     .08       0  436.17     .12       0
Bank Sta=336.3,362.4
XS Rating Curve= 0 ,0
Exp/Cntr=0.3,0.1

Type RM Length L Ch R = 1 ,16290.2 ,237.4,261.7,181.2
XS GIS Cut Line= 3
     2080642.105      255511.274     2080216.953      255506.953
     2079928.965      255629.995
#Sta/Elev= 30
       0 2113.55    26.2  2111.1    98.1 2111.48     121 2110.51  144.332108.546
   179.9 2105.42   186.4  2103.8   222.4 2097.19   255.1 2089.94   264.9 2089.16
   274.7 2087.33   291.1 2087.33   300.9 2084.53   304.2 2084.37   307.4 2084.72
   314.3  2087.3   317.2 2087.66   327.1 2087.37   336.9 2087.65   382.7  2087.2
   405.6 2089.77   464.3 2092.75   496.9 2098.69   516.5  2103.9   536.1 2107.21
   552.4 2110.61   601.3 2118.82   653.5 2125.65   686.2 2129.12   738.4 2133.36
#Mann= 4 ,-1 , 0
       0     .06       0  144.33     .12       0   291.1    .045       0
   314.3     .12       0
Bank Sta=291.1,314.3
XS Rating Curve= 0 ,0
Exp/Cntr=0.3,0.1

Type RM Length L Ch R = 1 ,16028.4 ,290.8,486.8,477.6
XS GIS Cut Line= 4
      2080561.81      255248.687     2080326.661      255308.355
     2080160.529      255452.699     2079908.793      255541.675
#Sta/Elev= 30
       0 2120.77   104.9 2113.66   167.2 2107.39   193.4 2103.18   232.8 2093.82
   249.1 2091.34   258.8 2087.04     262 2085.61   265.3 2084.77   268.5 2084.63
   271.7 2085.17   278.2 2087.33   297.6 2087.13   336.5 2087.57   365.6 2086.85
   391.5 2088.14   401.2 2089.09   414.1 2088.55   430.3 2089.07     453 2090.81
   469.2 2093.09     479 2095.38     518 2108.43   540.8 2115.54   550.6 2118.24
   573.4 2122.69   599.4 2126.96     658 2133.93   697.1 2139.15   729.7 2142.75
#Mann= 3 ,-1 , 0
       0     .06       0   258.8    .045       0   278.2     .12       0
Bank Sta=258.8,278.2
XS Rating Curve= 0 ,0
Exp/Cntr=0.3,0.1

Type RM Length L Ch R = 1 ,15541.6 ,62,58.3,56.1
XS GIS Cut Line= 5
     2080546.619      255172.732     2080154.453      255175.789
     2080096.424      255158.503      2080013.09      255155.899
     2079754.713      255417.977
#Sta/Elev= 30
       0 2118.53  180.28 2108.25   222.2 2105.36   258.2 2101.54   277.8 2100.48
   290.9 2098.57   326.8 2096.02   346.4 2092.78     366 2091.53   382.4 2091.73
   398.6 2090.05   413.42089.617   433.6 2088.57   455.9 2085.98  479.832085.634
   491.2 2085.41   500.8 2083.43   507.2 2083.86   513.6 2085.76  577.272090.459
  596.99 2091.98  630.312095.659  640.012097.282   685.9 2103.53   702.2 2107.05
   718.5 2112.12   731.5 2114.74  826.042130.966  866.632137.067   904.1 2141.81
#Mann= 12 ,-1 , 0
       0    .016       0  180.28     .06       0   413.4    .016       0
  479.83     .12       0   491.2    .045       0   513.6     .12       0
  577.27    .016       0  596.99     .06       0  630.31    .016       0
  640.01     .12       0  826.04     .06       0  866.63     .12       0
Bank Sta=491.2,513.6
XS Rating Curve= 0 ,0
Exp/Cntr=0.3,0.1

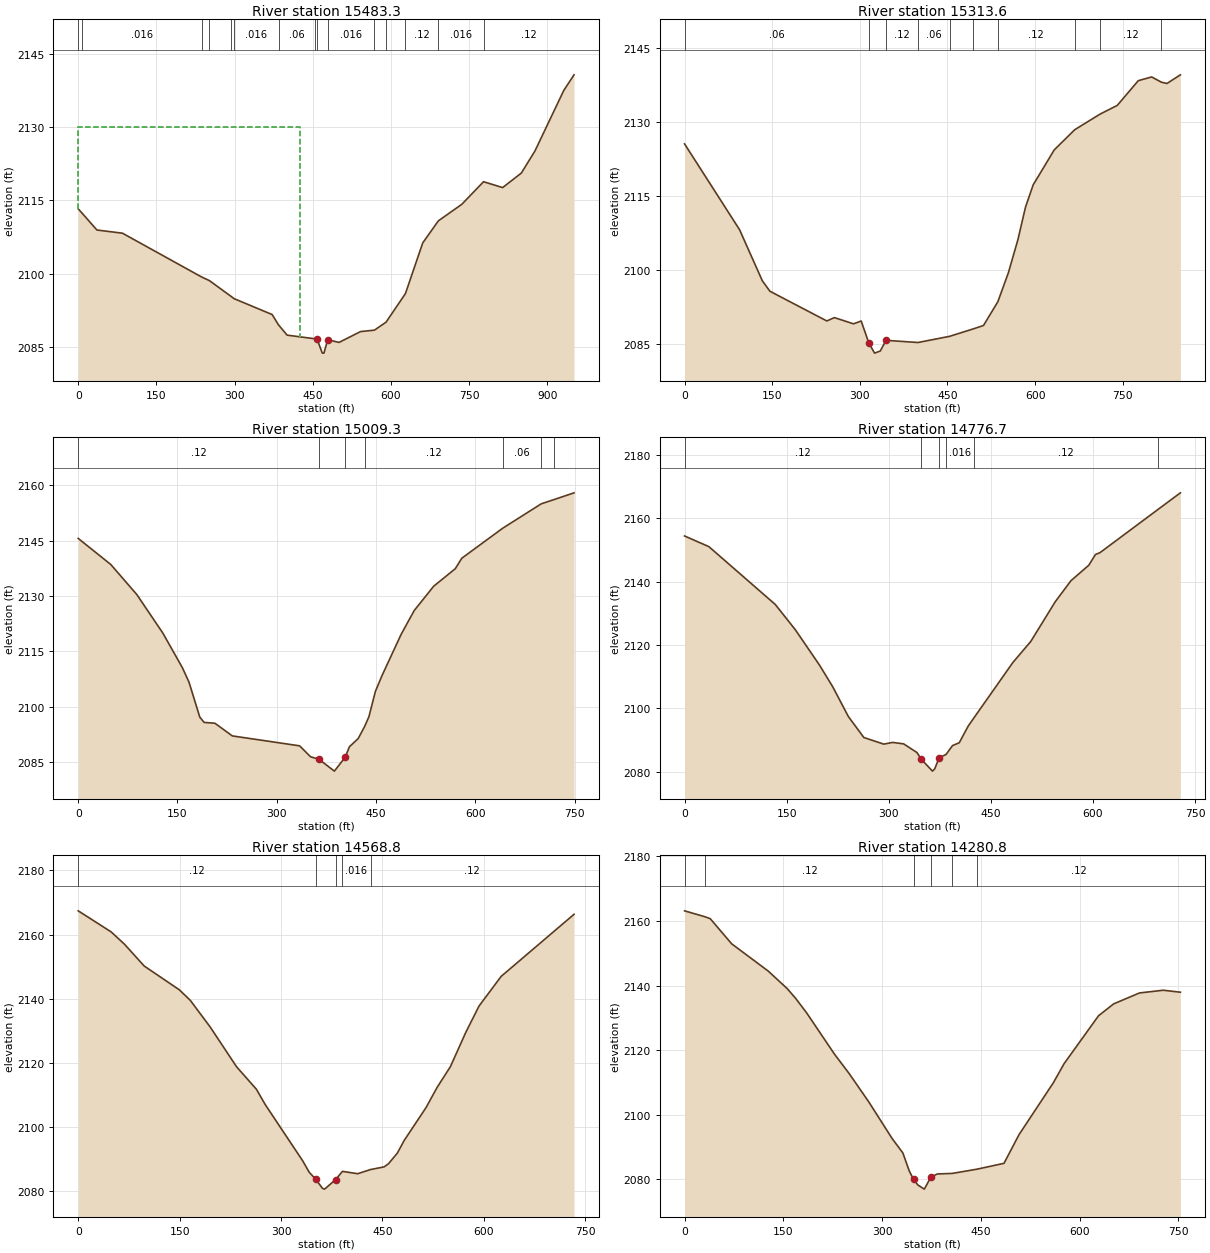
Type RM Length L Ch R = 1 ,15483.3 ,187.7,169.8,152.7
XS GIS Cut Line= 6
     2080553.129       255142.35     2080181.059      255138.972
     2080116.258       255121.97     2080035.529      255117.196
      2079986.05      255111.553     2079697.856      255361.553
#Sta/Elev= 30
       0 2113.25    7.132112.396    35.9 2108.91    84.9 2108.26  236.662099.309
  251.732098.563     2932095.358  299.062094.873   372.1 2091.62  384.322089.508
   400.8 2087.41  453.492086.671   458.5 2086.54   468.2 2083.75   471.4 2083.73
   478.8 2086.47   500.5 2085.92   541.7 2088.14   568.42088.429  590.722090.069
  627.822095.909     661 2106.27  690.95 2110.78     736 2114.17  777.682118.787
   814.3 2117.59   850.2 2120.56   876.3 2125.07   931.7 2137.47   951.3 2140.65
#Mann= 15 ,-1 , 0
       0     .06       0    7.13    .016       0  236.66     .06       0
  251.73    .016       0     293     .12       0  299.06    .016       0
  384.32     .06       0  453.49    .016       0   458.5    .045       0
   478.8    .016       0   568.4     .06       0  590.72    .016       0
  627.82     .12       0  690.95    .016       0  777.68     .12       0
#XS Ineff= 2 , 0
          424.97    2130
Permanent Ineff=
       F       F
Bank Sta=458.5,478.8
XS Rating Curve= 0 ,0
Exp/Cntr=0.3,0.1

Type RM Length L Ch R = 1 ,15313.6 ,290,304.3,296
XS GIS Cut Line= 3
     2080390.369      254792.958     2080178.758      254937.942
     2079659.661      255222.664
#Sta/Elev= 30
       0 2125.52    94.2 2108.14   133.1 2097.81   146.1 2095.69   243.5 2089.67
   256.5 2090.35   289.2 2089.09   302.3 2089.66   315.4 2085.22   325.2 2083.16
     335 2083.59   344.8 2085.75  399.582085.311  453.522086.556  494.242088.071
   511.6 2088.75  536.292093.583   554.2 2099.42   570.5 2106.11   583.6 2112.75
   596.7 2117.23   632.7  2124.3  667.682128.381  711.03 2131.54   740.6 2133.31
   776.6 2138.32   799.5 2139.07  815.952138.016   825.7 2137.75   848.6  2139.5
#Mann= 10 ,-1 , 0
       0     .06       0   315.4    .045       0   344.8     .12       0
  399.58     .06       0  453.52    .016       0  494.24     .06       0
  536.29     .12       0  667.68     .06       0  711.03     .12       0
  815.95    .016       0
Bank Sta=315.4,344.8
XS Rating Curve= 0 ,0
Exp/Cntr=0.3,0.1

Type RM Length L Ch R = 1 ,15009.3 ,217.7,232.6,248.9
XS GIS Cut Line= 3
     2080189.929      254568.999     2079902.249      254827.856
      2079631.33      255068.111
#Sta/Elev= 30
       0 2145.57    49.2 2138.52    88.6 2130.37   127.9 2119.95   157.4 2110.59
   167.3 2106.73   183.7 2097.22   190.2 2095.79   206.6 2095.56   232.8 2092.14
   334.5 2089.45   350.9 2086.51     364 2085.79     387 2082.61   403.3 2086.36
   409.8 2089.22   422.9 2091.39  432.652094.665   439.2 2097.32     449 2104.19
   458.8 2108.38   488.1 2119.69   507.7 2126.07   537.1 2132.64   569.7 2137.37
   579.5  2140.2  641.092148.292  699.562154.925  719.442156.104   749.1  2157.9
#Mann= 7 ,-1 , 0
       0     .12       0     364    .045       0   403.3    .016       0
  432.65     .12       0  641.09     .06       0  699.56     .12       0
  719.44     .06       0
Bank Sta=364,403.3
XS Rating Curve= 0 ,0
Exp/Cntr=0.3,0.1

Type RM Length L Ch R = 1 ,14776.7 ,219.6,208,194.3
XS GIS Cut Line= 3
     2080161.299      254489.279     2079818.926      254613.456
     2079469.478      254715.961
#Sta/Elev= 30
       0 2154.41    35.8 2151.03   133.3 2132.77   162.6 2124.83   198.4 2113.57
   217.9 2106.69   240.6 2097.38   263.4 2090.74   292.7 2088.65   305.7 2089.19
   321.9 2088.73   341.4    2086   347.9 2083.84   364.2 2080.12   367.5 2080.82
     374 2084.36  384.132085.374   393.7 2088.19   403.6 2089.09   416.7 2094.35
  424.64  2096.8   482.3 2114.43   508.6 2121.08   544.6 2133.64   567.6 2140.27
   593.8 2145.15   603.7 2148.57   610.3 2149.14  696.252162.904   728.4 2168.04
#Mann= 6 ,-1 , 0
       0     .12       0   347.9    .045       0     374     .12       0
  384.13    .016       0  424.64     .12       0  696.25     .06       0
Bank Sta=347.9,374
XS Rating Curve= 0 ,0
Exp/Cntr=0.3,0.1

Type RM Length L Ch R = 1 ,14568.8 ,274.6,288,294.4
XS GIS Cut Line= 3
     2080025.562      254199.877     2079711.744       254443.15
     2079423.485      254616.639
#Sta/Elev= 30
       0 2167.41    48.8 2160.83    68.4 2157.01    97.6  2150.2   149.7 2142.76
     166 2139.44   195.3 2131.16   234.3 2118.76   263.6 2111.76   276.6    2107
     332 2089.46   341.7 2085.88   351.5 2083.64   361.3 2080.86   364.5  2080.6
   380.8 2083.58   390.92086.144   413.4 2085.41  432.442086.704   452.6 2087.54
   459.1 2088.54   472.2 2091.86     482  2095.7   514.7 2106.08     531 2112.35
   550.6  2118.8   573.4 2129.51     593 2137.73   625.7 2146.96   733.5 2166.33
#Mann= 5 ,-1 , 0
       0     .12       0   351.5    .045       0   380.8     .12       0
   390.9    .016       0  432.44     .12       0
Bank Sta=351.5,380.8
XS Rating Curve= 0 ,0
Exp/Cntr=0.3,0.1

Type RM Length L Ch R = 1 ,14280.8 ,243,254.1,254.4
XS GIS Cut Line= 3
     2079998.534      254126.676     2079668.342      254156.692
     2079285.307      254332.764
#Sta/Elev= 30
       0 2163.13   31.612161.256      39  2160.7    71.5 2152.93   126.8 2144.52
     156 2139.04     169 2135.96   185.3 2131.57   227.5 2118.82   250.3 2112.66
   279.6 2104.03   315.3 2092.62   331.6 2088.15   341.4 2082.53   347.9 2079.95
   354.4 2078.22   364.2 2076.95     374 2080.62   383.8 2081.64  406.492081.813
  444.192083.126   485.2 2084.94     508 2093.81   560.3 2109.93   576.6 2115.84
   628.9 2130.66   651.8 2134.32     691  2137.7     727 2138.54   753.1 2137.93
#Mann= 6 ,-1 , 0
       0    .016       0   31.61     .12       0   347.9    .045       0
     374     .12       0  406.49    .016       0  444.19     .12       0
Bank Sta=347.9,374
XS Rating Curve= 0 ,0
Exp/Cntr=0.3,0.1

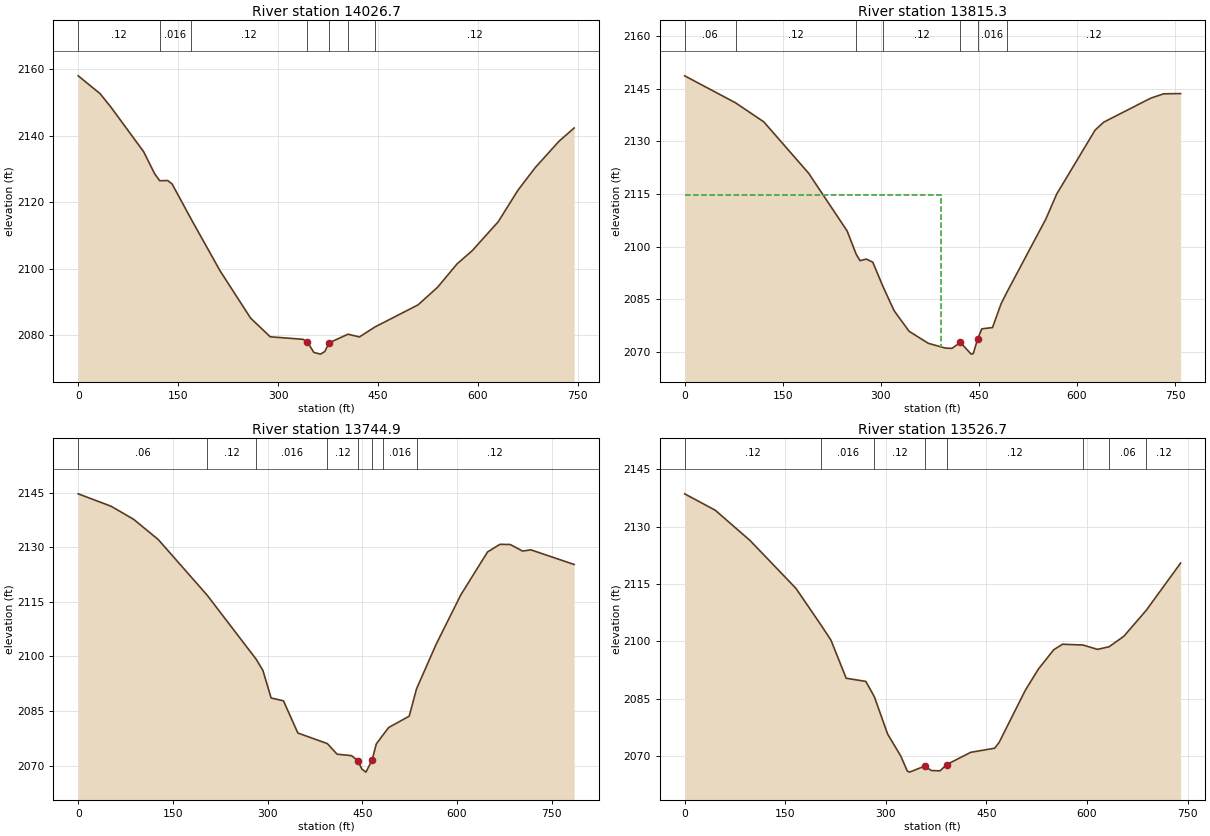
Type RM Length L Ch R = 1 ,14026.7 ,210.3,211.4,211
XS GIS Cut Line= 3
     2079871.383      253828.975     2079546.195      253984.349
     2079195.229      254140.759
#Sta/Elev= 30
       0 2157.94    32.8 2152.59    49.2 2148.52    98.3 2135.12   114.7 2128.54
  122.352126.417   134.3 2126.48   140.9 2125.47  169.352114.973     213 2099.35
   258.8 2085.15   288.3 2079.53   337.5 2078.77     344 2077.99   353.8 2074.83
   363.7 2074.32   370.2  2075.1   376.7 2077.71  405.042080.306   422.3 2079.49
  445.432082.467   510.2 2089.12   539.5  2094.4   568.8 2101.43   591.6 2105.41
   630.7 2114.12     660  2123.5     686 2130.33   721.8 2138.27   744.6 2142.27
#Mann= 7 ,-1 , 0
       0     .12       0  122.35    .016       0  169.35     .12       0
     344    .045       0   376.7     .12       0  405.04    .016       0
  445.43     .12       0
Bank Sta=344,376.7
XS Rating Curve= 0 ,0
Exp/Cntr=0.3,0.1

Type RM Length L Ch R = 1 ,13815.3 ,72.5,70.4,70.3
XS GIS Cut Line= 2
     2079812.439      253644.539     2079119.731      253953.567
#Sta/Elev= 30
       0 2148.74   77.822141.034     121  2135.6   189.6 2120.93   248.5 2104.44
  262.142097.875   268.1 2095.97   277.9 2096.41   287.7 2095.53  303.212088.614
   320.4 2081.65   343.3 2075.79   372.7 2072.36   398.9    2071   408.7 2070.92
   421.8 2072.61   438.1 2069.28   441.4 2069.43   447.9 2073.52   454.4  2076.5
   470.8 2076.87   483.9 2083.66  492.742086.928   552.5  2107.9   568.9 2114.96
   627.7 2133.24   640.8  2135.5   712.7 2142.35   732.4  2143.6   758.5 2143.67
#Mann= 7 ,-1 , 0
       0     .06       0   77.82     .12       0  262.14    .016       0
  303.21     .12       0   421.8    .045       0   447.9    .016       0
  492.74     .12       0
#XS Ineff= 2 , 0
          391.42 2114.72
Permanent Ineff=
       F       F
Bank Sta=421.8,447.9
XS Rating Curve= 0 ,0
Exp/Cntr=0.3,0.1

Type RM Length L Ch R = 1 ,13744.9 ,198.2,218.2,236.5
XS GIS Cut Line= 3
     2079808.967      253604.609     2079509.298      253702.934
       2079079.8      253894.539
#Sta/Elev= 30
       0 2144.64      52 2141.24    87.8 2137.64   126.8 2132.09  204.442116.779
  282.03  2099.2   292.6 2096.15   305.6 2088.59   325.2 2087.79     348 2078.96
  394.63 2076.06   410.1 2073.15     433 2072.74   442.8 2071.41   449.3 2069.09
   455.8 2068.22   465.6 2071.51   472.2 2075.94  482.622078.374   491.8 2080.46
   524.4 2083.59  535.99 2091.09   566.9 2103.27   606.1 2116.88   648.5 2128.68
   668.1 2130.77   684.4 2130.73     704 2128.92   717.1 2129.26   785.7 2125.24
#Mann= 8 ,-1 , 0
       0     .06       0  204.44     .12       0  282.03    .016       0
  394.63     .12       0   442.8    .045       0   465.6     .12       0
  482.62    .016       0  535.99     .12       0
Bank Sta=442.8,465.6
XS Rating Curve= 0 ,0
Exp/Cntr=0.3,0.1

Type RM Length L Ch R = 1 ,13526.7 ,248.9,250,248.9
XS GIS Cut Line= 3
     2079802.024      253572.255     2079427.868      253559.845
     2079063.199      253537.122
#Sta/Elev= 30
       0 2138.56    45.6 2134.27    97.7 2126.32     166 2113.82  203.252104.263
   218.1 2100.32   240.9 2090.32   270.2 2089.49     2832085.446   302.7 2075.72
   322.3 2069.98     332 2066.06   335.3 2065.76   358.1 2067.34   367.8 2066.18
   380.9  2066.1   390.7 2067.72   426.6 2070.94   462.4 2072.02     469 2073.53
   508.1 2087.18   527.7 2092.75   550.5 2097.78   563.6 2099.22  594.072099.011
   615.8 2097.87  633.022098.553   654.9 2101.28  688.512108.108   739.7 2120.45
#Mann= 8 ,-1 , 0
       0     .12       0  203.25    .016       0     283     .12       0
   358.1    .045       0   390.7     .12       0  594.07    .016       0
  633.02     .06       0  688.51     .12       0
Bank Sta=358.1,390.7
XS Rating Curve= 0 ,0
Exp/Cntr=0.3,0.1