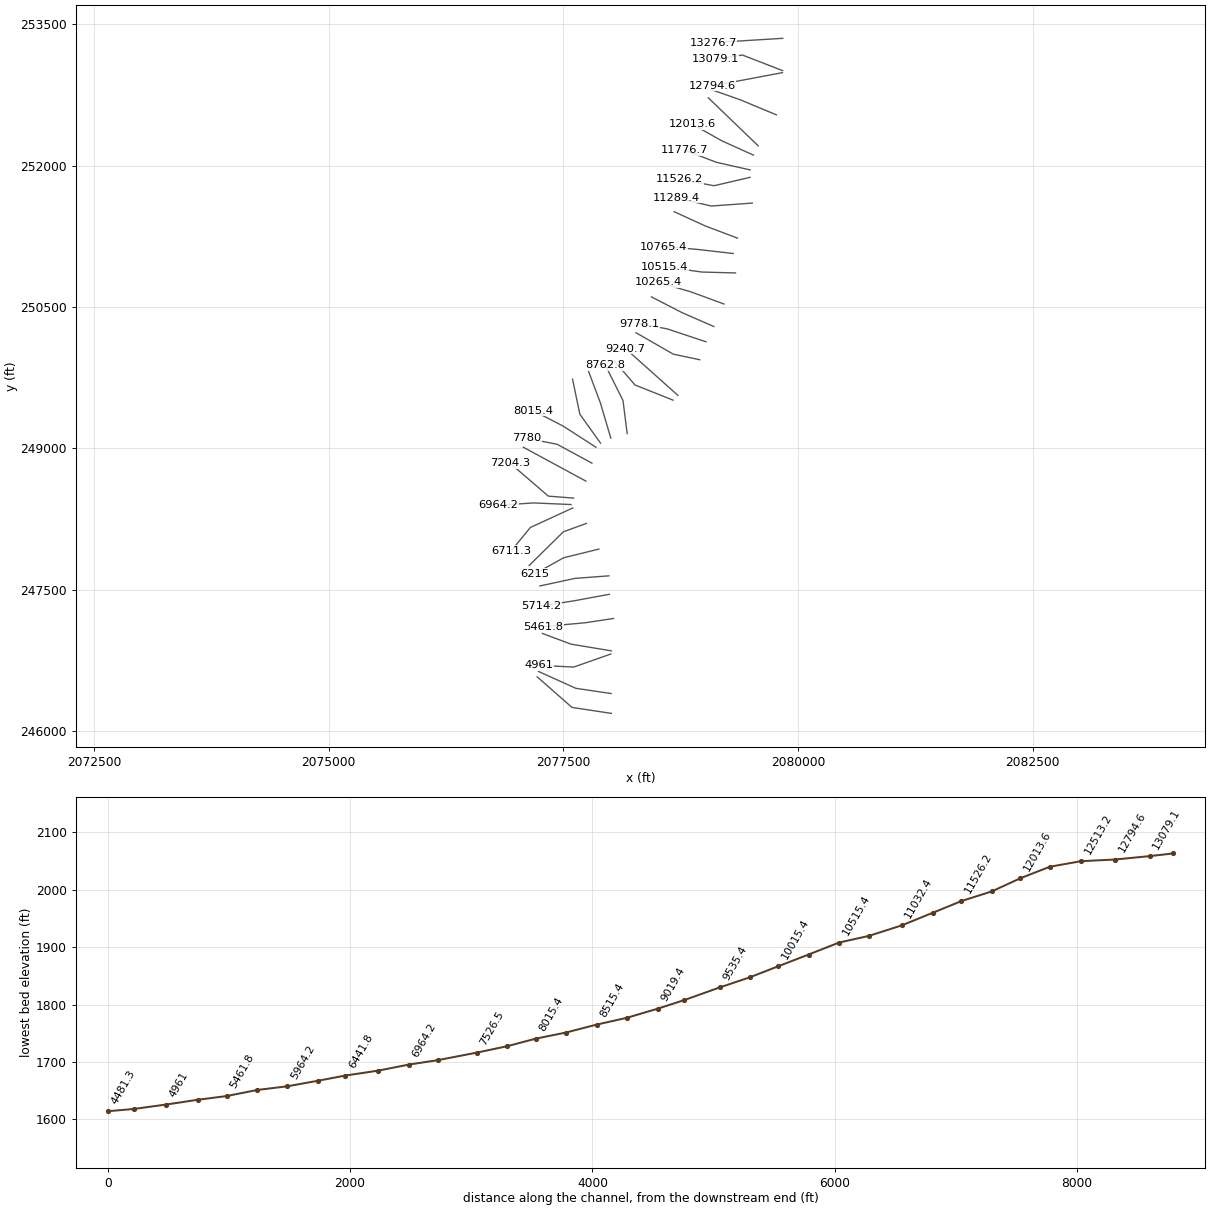
HEC-RAS study LAURELCK4.prj: LAURELCK4

--- LAURELCK4.g01 (geometry) --- (continued)

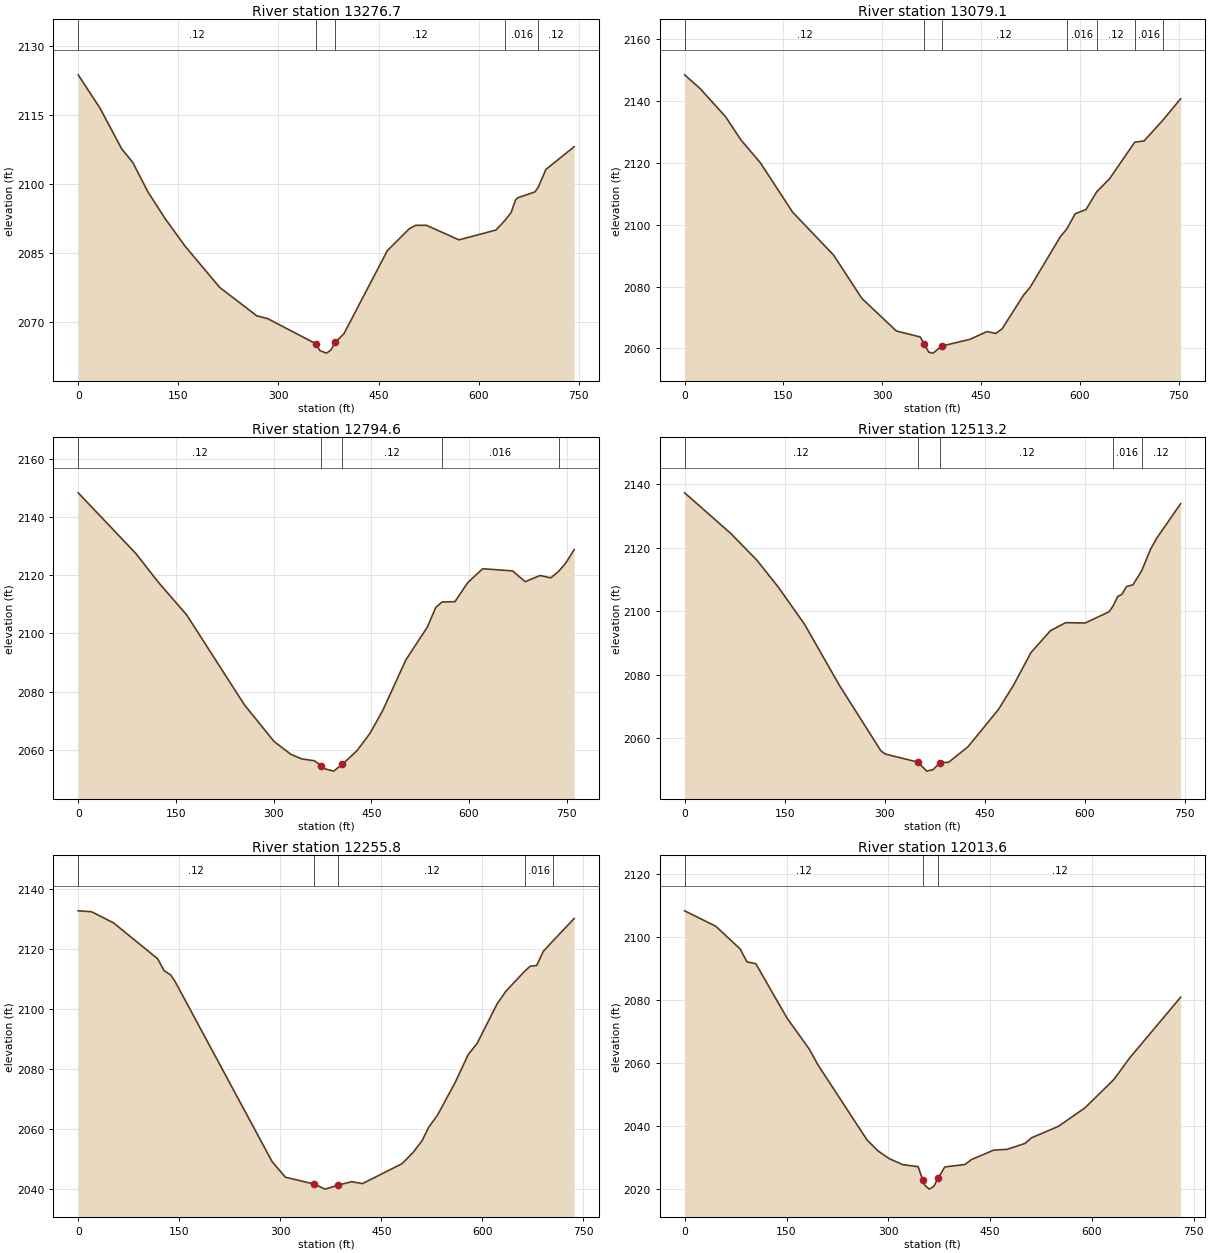
Type RM Length L Ch R = 1 ,13276.7 ,211.5,197.6,180.9
XS GIS Cut Line= 3
      2079836.43      253351.651      2079465.13      253329.115
     2079094.971      253305.476
#Sta/Elev= 30
       0  2123.8    32.6 2116.56    65.3 2107.66    81.6 2104.78   104.4 2098.34
   130.5 2092.46   159.9 2086.56   212.1 2077.53   267.6 2071.37   283.9 2070.76
   355.7 2065.32   362.2 2063.79     372 2063.26   378.5 2063.94     385 2065.61
     398 2067.47   463.1 2085.56   495.6 2090.27   505.4 2091.06   521.6 2091.07
   570.4  2087.9   625.8 2090.04   639.42092.147   648.5 2093.84     655 2096.54
   658.3 2097.05   684.3 2098.34  689.272099.397   700.6 2103.22   742.9 2108.16
#Mann= 5 ,-1 , 0
       0     .12       0   355.7    .045       0     385     .12       0
   639.4    .016       0  689.27     .12       0
Bank Sta=355.7,385
XS Rating Curve= 0 ,0
Exp/Cntr=0.3,0.1

Type RM Length L Ch R = 1 ,13079.1 ,254.8,284.5,305.6
XS GIS Cut Line= 3
     2079835.008      253009.123     2079406.754       253174.36
     2079116.258       253130.65
#Sta/Elev= 30
       0 2148.32      23 2143.98    62.3 2134.74    85.2 2127.37   114.8 2119.96
   163.9 2103.98   226.2 2090.11   268.9 2076.17   321.3 2065.65   357.4 2063.73
   363.9 2061.42   370.5  2058.8   377.1  2058.5   390.2 2060.78   432.8 2062.94
     459 2065.46   472.1 2064.85   481.9 2066.36   514.5 2077.25   524.3 2079.73
     570    2096   579.72098.473   592.8  2103.5   609.2 2104.84  625.352110.548
   645.1 2114.82  683.142126.575   697.3 2126.98  726.31 2133.79   752.8  2140.6
#Mann= 7 ,-1 , 0
       0     .12       0   363.9    .045       0   390.2     .12       0
   579.7    .016       0  625.35     .12       0  683.14    .016       0
  726.31     .12       0
Bank Sta=363.9,390.2
XS Rating Curve= 0 ,0
Exp/Cntr=0.3,0.1

Type RM Length L Ch R = 1 ,12794.6 ,303.7,281.4,257.3
XS GIS Cut Line= 2
     2079833.426      252987.615      2079085.02      252846.847
#Sta/Elev= 30
       0 2148.38    88.2 2127.59   124.2 2117.31   166.7 2106.33   254.9 2075.54
   300.7 2062.83   326.8 2058.38   343.2 2056.84   362.8 2056.19   372.6 2054.56
   379.1  2053.4   392.2 2052.63   405.3 2054.93   428.2  2059.7   447.8 2065.56
   467.4  2073.4   503.3 2090.97     536 2102.16   549.1 2108.99  558.642110.821
   578.5 2110.94   598.1 2117.49     621 2122.26   666.8 2121.53   686.4 2117.81
   709.2 2119.94   725.6 2119.12   737.62121.347   748.5 2124.17   761.5 2128.84
#Mann= 5 ,-1 , 0
       0     .12       0   372.6    .045       0   405.3     .12       0
  558.64    .016       0   737.6     .12       0
Bank Sta=372.6,405.3
XS Rating Curve= 0 ,0
Exp/Cntr=0.3,0.1

Type RM Length L Ch R = 1 ,12513.2 ,270.3,257.4,242.6
XS GIS Cut Line= 3
     2079767.825       252539.49     2079390.564      252696.623
     2079074.592      252807.734
#Sta/Elev= 30
       0 2137.23    68.7 2124.54   107.9 2116.14   140.6 2107.52   179.8 2095.88
   232.1 2076.67   294.2 2056.12   300.8  2055.1   349.8 2052.55   362.9 2049.73
   372.7 2050.21   382.5 2052.38   395.6  2052.5   424.9 2057.41   470.5 2069.13
   493.2 2076.81   519.2    2087   548.5 2093.91   571.3 2096.41   600.5 2096.29
   636.3 2099.84  642.172101.583   649.3 2104.64   655.8 2105.36   662.3 2107.74
   672.1 2108.32  685.37 2112.77   698.1 2119.31   707.8 2122.98   743.6 2133.81
#Mann= 5 ,-1 , 0
       0     .12       0   349.8    .045       0   382.5     .12       0
  642.17    .016       0  685.37     .12       0
Bank Sta=349.8,382.5
XS Rating Curve= 0 ,0
Exp/Cntr=0.3,0.1

Type RM Length L Ch R = 1 ,12255.8 ,229.7,242.2,252.1
XS GIS Cut Line= 2
     2079574.592      252210.512     2079043.276      252720.145
#Sta/Elev= 30
       0 2132.83    19.6 2132.54    52.4 2128.82   117.8 2116.86   127.6 2112.85
   137.4 2111.41     144 2109.17   287.9 2049.12   307.6 2043.94   350.1 2041.66
   366.5 2039.97   386.1 2041.31   405.7 2042.44   422.1 2041.82     481  2048.5
   497.4  2052.3   510.4 2056.12   520.3 2060.62   533.4 2064.67   559.5 2075.53
   579.2 2084.96   592.2 2088.61   621.7 2101.72   634.8 2105.99  663.122112.761
   670.8 2114.33   680.6 2114.61   690.4 2119.31  704.542122.753   736.2 2130.26
#Mann= 5 ,-1 , 0
       0     .12       0   350.1    .045       0   386.1     .12       0
  663.12    .016       0  704.54     .12       0
Bank Sta=350.1,386.1
XS Rating Curve= 0 ,0
Exp/Cntr=0.3,0.1

Type RM Length L Ch R = 1 ,12013.6 ,228.8,236.9,241.6
XS GIS Cut Line= 3
     2079523.873      252112.228     2079189.278      252262.685
     2078871.932      252440.186
#Sta/Elev= 30
       0 2108.41    45.9  2103.5    81.9 2096.26    91.7 2092.21   104.8 2091.61
   150.7 2074.37   183.4 2064.53   196.5 2059.43   268.6 2035.65     285 2032.13
   301.4  2029.7     321 2027.83   343.9 2027.15   350.5 2023.02   353.8 2021.24
   360.3 2020.03   366.9 2020.89   373.4  2023.6   383.2 2027.08   412.7 2027.84
   422.6 2029.44   455.3 2032.42     475 2032.66   501.2 2034.54     511 2036.34
   550.3 2039.94   589.6 2045.84   632.2 2054.85   655.1  2061.6   730.5 2080.97
#Mann= 3 ,-1 , 0
       0     .12       0   350.5    .045       0   373.4     .12       0
Bank Sta=350.5,373.4
XS Rating Curve= 0 ,0
Exp/Cntr=0.3,0.1

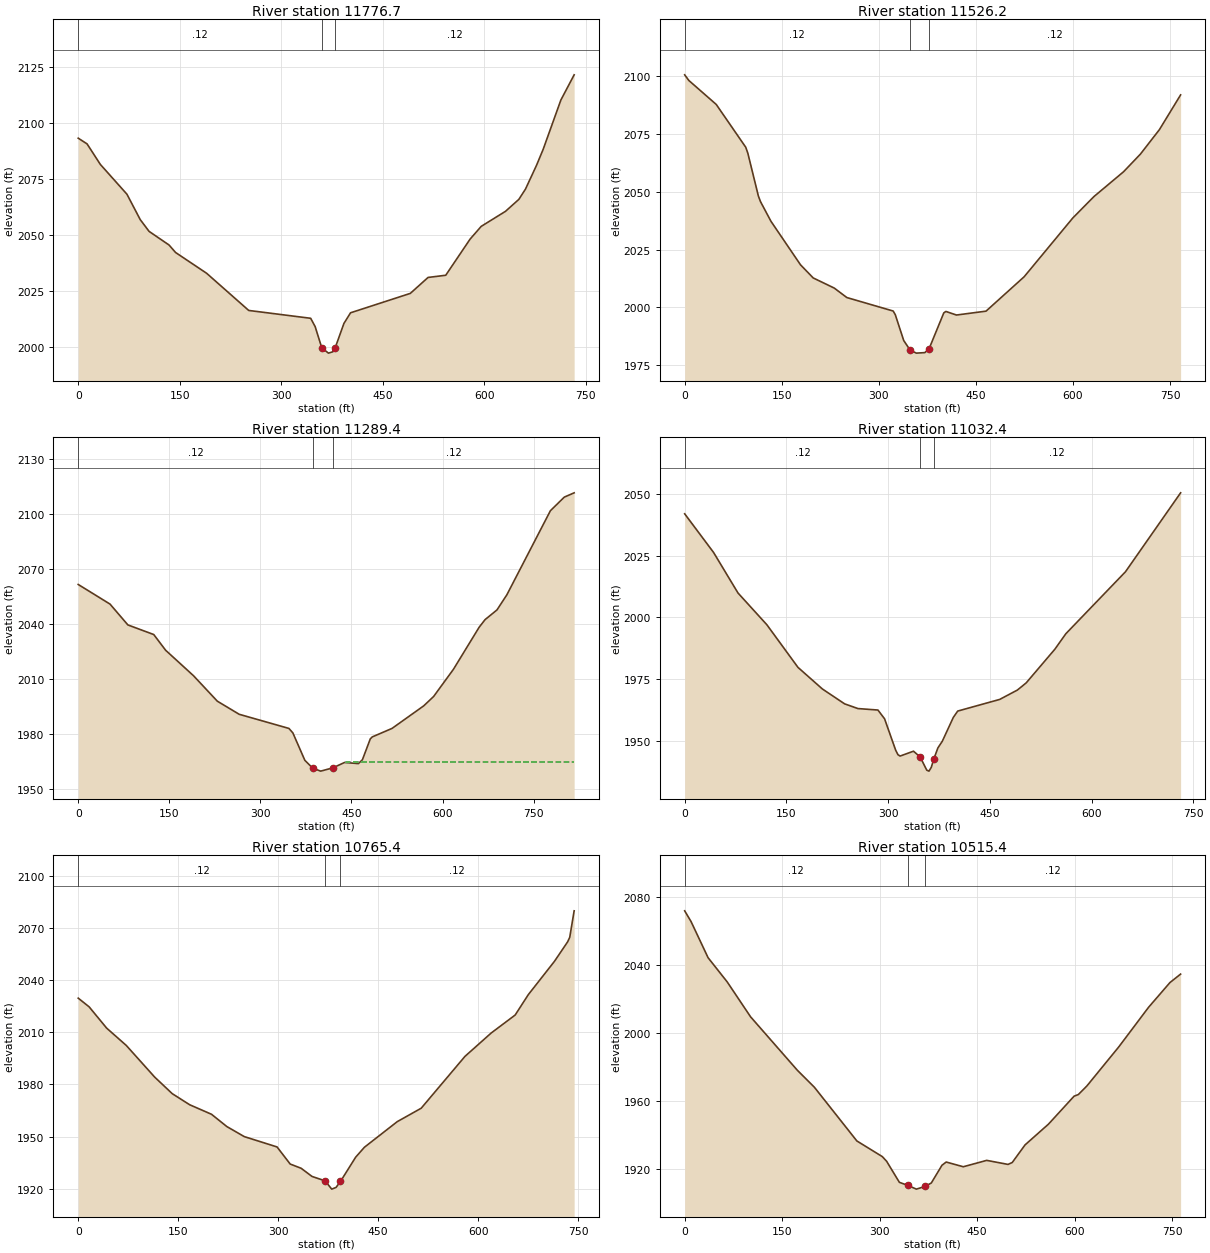
Type RM Length L Ch R = 1 ,11776.7 ,233.5,250.5,268.3
XS GIS Cut Line= 3
     2079488.724      251954.804     2079128.167      252036.108
     2078788.938      252165.335
#Sta/Elev= 30
       0 2093.25    13.1 2090.68    32.7  2081.5      72 2068.16    91.6 2056.81
   104.7 2051.53   134.1 2045.45   143.9 2042.07   189.7 2032.78   251.9 2016.14
   343.4 2012.63     350 2008.92   359.8 1999.42   369.6 1997.04   376.2 1997.65
   379.4 1999.26   392.5 2010.32   402.3 2015.09   490.6 2023.78   516.8 2030.91
   542.9 2031.89   578.9 2048.07   595.3 2053.77   631.2 2060.51   650.9 2065.85
   660.7 2070.45     677 2081.09   686.8 2088.23     713 2110.33   732.6  2121.6
#Mann= 3 ,-1 , 0
       0     .12       0   359.8    .045       0   379.4     .12       0
Bank Sta=359.8,379.4
XS Rating Curve= 0 ,0
Exp/Cntr=0.3,0.1

Type RM Length L Ch R = 1 ,11526.2 ,242.4,236.8,233.2
XS GIS Cut Line= 3
     2079487.748      251875.991     2079104.106        251786.9
     2078737.786      251854.609
#Sta/Elev= 30
       0 2100.54     6.5 2098.08    48.8 2087.73    94.4 2069.22    97.6 2066.66
   113.9 2048.14   117.2  2045.7   133.4 2037.19     179 2018.41   198.6 2012.73
   231.1 2008.35   250.6 2004.25   322.2 1998.42   325.5 1996.82   338.5 1985.67
   348.3 1981.57     358 1980.22   371.1 1980.44   377.6 1982.05   400.4  1997.6
   403.6 1998.25     420 1996.69   465.7 1998.37   524.6 2013.23   599.7 2038.62
   632.4 2047.89   678.2 2058.63   704.3 2066.27   733.7 2076.87   766.4 2091.87
#Mann= 3 ,-1 , 0
       0     .12       0   348.3    .045       0   377.6     .12       0
Bank Sta=348.3,377.6
XS Rating Curve= 0 ,0
Exp/Cntr=0.3,0.1

Type RM Length L Ch R = 1 ,11289.4 ,272.3,257,239.6
XS GIS Cut Line= 3
     2079511.247      251602.699     2079073.747      251571.449
     2078705.836      251658.474
#Sta/Elev= 30
       0 2061.54    52.4 2050.85    81.8 2039.49   124.4 2034.25     144 2025.68
   189.8 2011.83   229.1 1997.93   265.1 1990.79     347 1983.08   353.5 1980.64
   373.2 1965.72   386.2 1961.39   399.3 1959.81     419 1961.56   438.6 1964.52
   461.4 1963.91     468    1966     481 1977.38   484.2 1978.45   516.8 1983.09
     569 1995.39   585.3 2000.49   617.9  2015.3   660.2  2038.2     670 2042.38
   689.6 2047.66   705.9 2055.91   777.6 2101.74   800.4 2109.13   816.7 2111.49
#Mann= 3 ,-1 , 0
       0     .12       0   386.2    .045       0     419     .12       0
#XS Ineff= 2 , 0
                          441.76         1964.74
Permanent Ineff=
       F       F
Bank Sta=386.2,419
XS Rating Curve= 0 ,0
Exp/Cntr=0.3,0.1

Type RM Length L Ch R = 1 ,11032.4 ,257.1,267.1,279.1
XS GIS Cut Line= 3
       2079353.5      251230.843      2079010.31      251360.202
     2078678.908      251511.523
#Sta/Elev= 30
       0 2041.96    42.6 2026.32    78.6 2009.91   121.2 1997.04     167  1979.8
     203 1971.05   235.8 1965.02   255.4 1963.12   284.9 1962.52   294.7 1958.97
   311.1 1946.22   314.4 1944.45   317.6 1943.89   337.3 1945.86   347.1 1943.53
   356.9 1938.18   360.2 1937.79   363.5 1939.31   367.1 1942.54   373.3  1947.2
   379.8  1949.9     396 1959.52   402.5  1962.1   464.4 1966.82   490.4  1970.6
   503.4  1973.5   545.7 1987.14   561.9 1993.41   649.8  2018.5   731.1 2050.46
#Mann= 3 ,-1 , 0
       0     .12       0   347.1    .045       0   367.1     .12       0
Bank Sta=347.1,367.1
XS Rating Curve= 0 ,0
Exp/Cntr=0.3,0.1

Type RM Length L Ch R = 1 ,10765.4 ,246.6,250,246.5
XS GIS Cut Line= 3
     2079308.706      251067.216     2078927.663      251110.904
       2078568.5      251141.567
#Sta/Elev= 30
       0 2029.56    16.4 2024.55    42.6 2012.35    72.1 2002.37   114.7 1984.17
     141 1974.66   167.2 1968.27     200 1962.78   222.9 1955.74   249.1 1949.95
   298.3    1944     318 1934.17   334.4 1931.75   350.8 1927.03   370.4 1924.52
   380.3 1919.75   386.8 1920.73   393.4 1924.14   416.3 1938.15   429.4 1943.84
   478.6 1958.54   514.6 1966.28   580.2 1996.07   619.5 2009.49   655.5 2019.84
   675.2 2031.55   714.5 2050.74   734.2 2061.92   737.4 2064.55     744 2079.76
#Mann= 3 ,-1 , 0
       0     .12       0   370.4    .045       0   393.4     .12       0
Bank Sta=370.4,393.4
XS Rating Curve= 0 ,0
Exp/Cntr=0.3,0.1

Type RM Length L Ch R = 1 ,10515.4 ,261.5,250,244.7
XS GIS Cut Line= 3
     2079332.809      250861.047     2078976.488      250870.419
     2078574.008      250926.959
#Sta/Elev= 30
       0 2072.07     9.8 2065.75      36 2044.42    65.4 2030.15   101.4 2009.54
   173.3 1978.04   199.5 1968.02   264.9 1936.32   304.1 1927.07   310.7 1924.31
   330.3 1911.91   343.4 1910.11   356.4 1907.91   369.6 1909.49   379.4 1911.53
   395.8 1921.99   402.3 1923.89   428.6 1921.11   464.6 1924.87   497.4 1922.49
   503.9 1923.62   523.6    1934   559.7 1946.27     599 1962.73   605.6  1963.7
   618.7 1968.76   667.8 1991.82   713.7 2015.21   746.5 2029.76   762.9 2034.75
#Mann= 3 ,-1 , 0
       0     .12       0   343.4    .045       0   369.6     .12       0
Bank Sta=343.4,369.6
XS Rating Curve= 0 ,0
Exp/Cntr=0.3,0.1

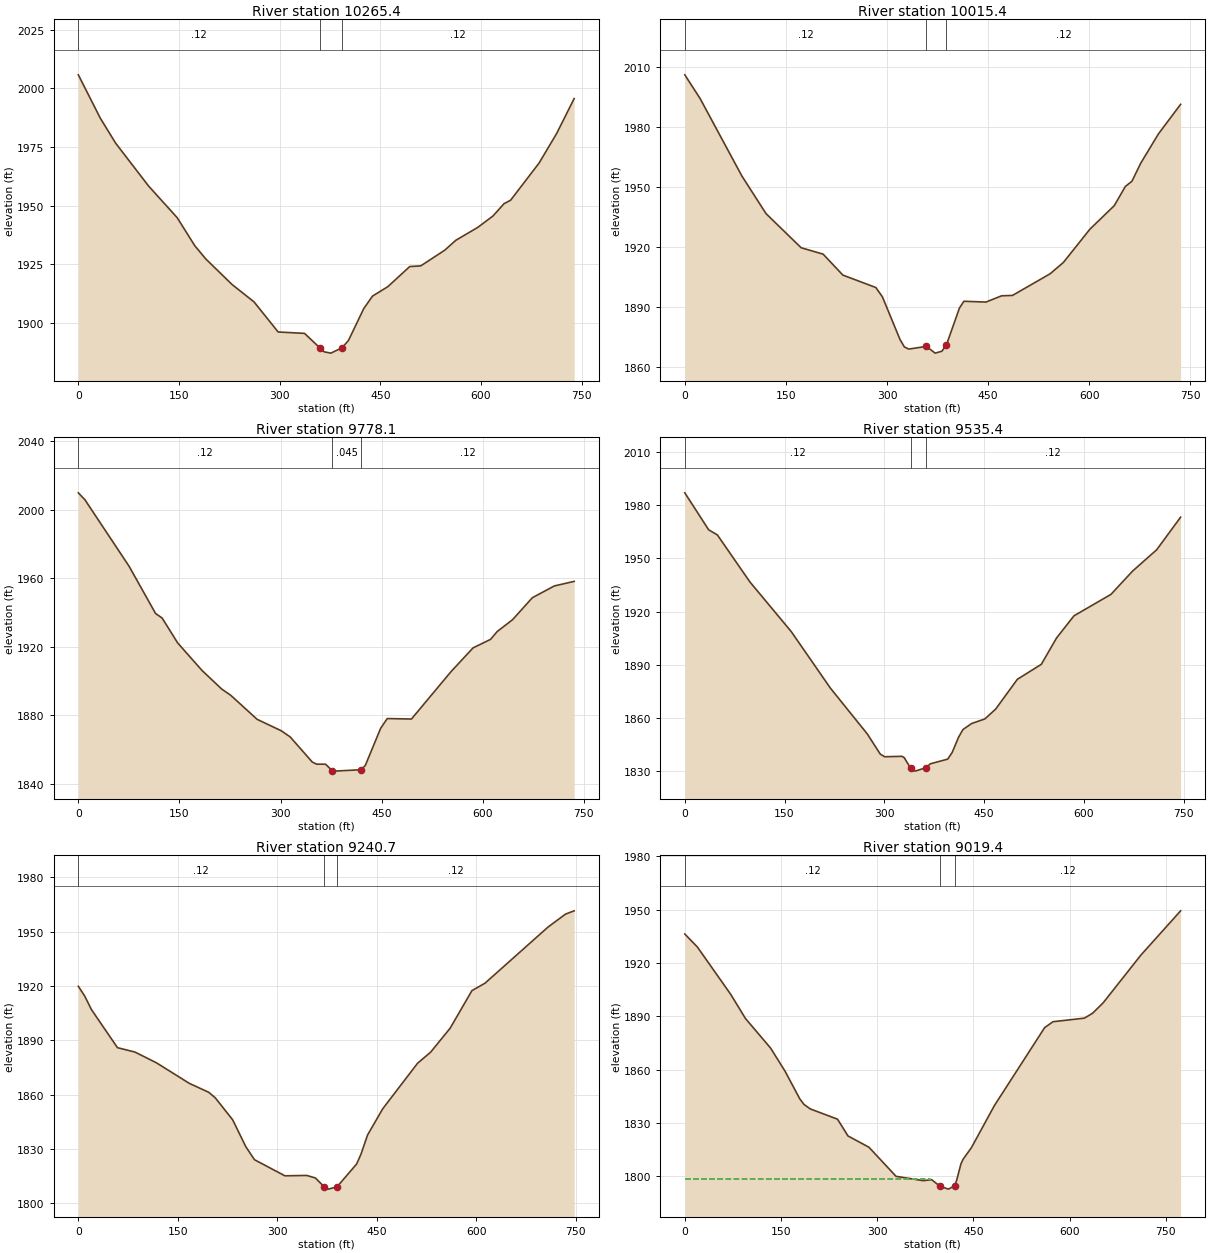
Type RM Length L Ch R = 1 ,10265.4 ,252.6,250,241.4
XS GIS Cut Line= 3
     2079209.417       250531.68     2078855.883      250660.771
     2078507.766      250761.961
#Sta/Elev= 30
       0 2005.79    32.7 1987.33    55.6 1976.66   104.7 1958.38   147.3 1944.89
   173.5 1932.95   189.8 1927.33   229.1 1916.39   261.8 1908.99   297.8 1896.14
   337.1 1895.55     360 1889.37   366.6 1887.66   376.4 1887.13   392.7 1889.36
   402.5 1892.49   425.4 1906.15   438.4 1911.45   461.3 1915.48   493.9 1924.05
   510.3 1924.33   546.2 1931.05   562.5 1935.23   595.2 1940.73     618 1945.62
   634.4 1950.85   644.2 1952.33   686.6 1968.16   712.8 1980.77   738.9 1995.66
#Mann= 3 ,-1 , 0
       0     .12       0     360    .045       0   392.7     .12       0
Bank Sta=360,392.7
XS Rating Curve= 0 ,0
Exp/Cntr=0.3,0.1

Type RM Length L Ch R = 1 ,10015.4 ,233.5,237.3,245.2
XS GIS Cut Line= 3
     2079102.084       250292.44     2078761.543      250440.525
     2078437.618      250606.889
#Sta/Elev= 30
       0  2006.3    22.8 1994.36    84.7 1955.57   120.5 1936.72   172.6 1919.61
   205.2  1916.4   234.5  1905.9   283.4 1899.67   293.2 1894.96   319.2 1873.66
   325.7 1869.89   332.3 1868.81   358.3 1870.15   371.4 1866.78   381.2 1867.71
   387.8 1870.62   407.4 1889.36     414 1892.78   446.8 1892.38   469.8  1895.5
   486.2 1895.72   541.9 1906.56   561.6 1912.24     601 1928.94   637.1 1940.72
   653.5 1950.34   663.3 1952.95   676.4 1962.05   702.7 1976.74   735.5 1991.52
#Mann= 3 ,-1 , 0
       0     .12       0   358.3    .045       0   387.8     .12       0
Bank Sta=358.3,387.8
XS Rating Curve= 0 ,0
Exp/Cntr=0.3,0.1

Type RM Length L Ch R = 1 ,9778.1  ,249.5,242.7,233.3
XS GIS Cut Line= 3
     2079018.191      250130.477     2078604.743      250267.249
     2078309.858      250323.185
#Sta/Elev= 30
       0 2009.93     9.8 2005.86    75.3 1967.02   114.6 1939.41   124.4 1936.73
   147.3 1922.25   183.4 1906.17   212.8 1895.23   225.9 1891.68   265.2 1877.58
   301.2 1870.85   314.3 1867.29   347.1 1852.58   353.6 1851.35   366.7 1851.34
   376.6 1847.63   379.8 1847.29   419.1  1848.1   425.7 1850.55   448.5  1872.3
   458.3 1878.02   494.2 1877.73   552.9 1905.43   585.6 1919.31   611.6  1924.3
   621.4 1928.86   644.3 1935.81   673.6 1948.64   706.3 1955.52   735.6 1958.18
#Mann= 3 ,-1 , 0
       0     .12       0   376.6    .045       0   419.1     .12       0
Bank Sta=376.6,419.1
XS Rating Curve= 0 ,0
Exp/Cntr=0.3,0.1

Type RM Length L Ch R = 1 ,9535.4  ,300.1,294.7,286.3
XS GIS Cut Line= 3
     2078952.219      249939.505     2078670.969      249998.532
     2078273.399      250225.963
#Sta/Elev= 30
       0 1986.97    35.9 1966.12      49 1963.24      98 1936.69     160 1908.78
   218.8 1876.94   274.3  1851.1   293.9 1839.69   300.5 1838.22   326.6 1838.46
   329.9 1837.69   339.7 1831.62   346.3 1830.11   362.6 1832.05   369.2 1834.25
   395.3 1836.88   401.9 1840.59   411.7 1849.32   418.2 1853.55   431.3 1856.97
     451  1859.5   467.3 1865.06     500 1881.88     536 1890.31   558.9 1905.18
   585.1 1917.65   640.7 1929.74   673.4 1942.94   709.4 1954.87   745.4 1973.24
#Mann= 3 ,-1 , 0
       0     .12       0   339.7    .045       0   362.6     .12       0
Bank Sta=339.7,362.6
XS Rating Curve= 0 ,0
Exp/Cntr=0.3,0.1

Type RM Length L Ch R = 1 ,9240.7  ,207.5,221.3,228.6
XS GIS Cut Line= 2
      2078719.58      249561.032     2078161.236      250057.847
#Sta/Elev= 30
       0 1919.91     9.8  1914.4    19.7 1907.08      59 1886.02    85.2 1883.61
     118 1877.61   167.2 1866.33   196.7 1861.36   206.5  1858.3   232.7 1846.16
   252.4  1831.4   265.5 1824.17   311.4 1815.27   344.2 1815.48   357.3 1814.09
   370.4 1809.29     377 1807.92   390.1 1809.25   419.6 1821.84   426.1 1827.24
     436 1837.82   458.9 1852.31   511.4 1877.43     531  1883.5   560.5 1896.78
   593.3  1917.5     613 1921.61     708 1952.59   734.3 1959.73   747.4 1961.56
#Mann= 3 ,-1 , 0
       0     .12       0   370.4    .045       0   390.1     .12       0
Bank Sta=370.4,390.1
XS Rating Curve= 0 ,0
Exp/Cntr=0.3,0.1

Type RM Length L Ch R = 1 ,9019.4  ,296.2,256.6,226.9
XS GIS Cut Line= 3
     2078667.497      249510.685     2078261.247      249672.144
     2078042.497      249927.352
#Sta/Elev= 30
       0 1936.29    19.6    1929    71.8 1902.26    94.6 1888.78   133.8 1872.15
   156.6 1858.99   179.4 1843.53     186 1840.41   195.7 1837.92   238.2 1832.15
   254.5 1822.72   287.1  1816.4   329.5    1800   371.9 1797.56     385 1798.12
     398 1794.43   411.1 1792.81   420.8 1794.68   424.1 1797.89   430.6 1806.92
   433.9 1809.53     447 1816.12   482.8 1839.76   561.2 1883.62   574.2 1886.96
   623.2 1888.97   636.2 1891.78   652.5 1897.59   711.3 1924.42   773.3 1949.33
#Mann= 3 ,-1 , 0
       0     .12       0     398    .045       0   420.8     .12       0
#XS Ineff= 2 , 0
          382.06  1798.3
Permanent Ineff=
       F       F
Bank Sta=398,420.8
XS Rating Curve= 0 ,0
Exp/Cntr=0.3,0.1

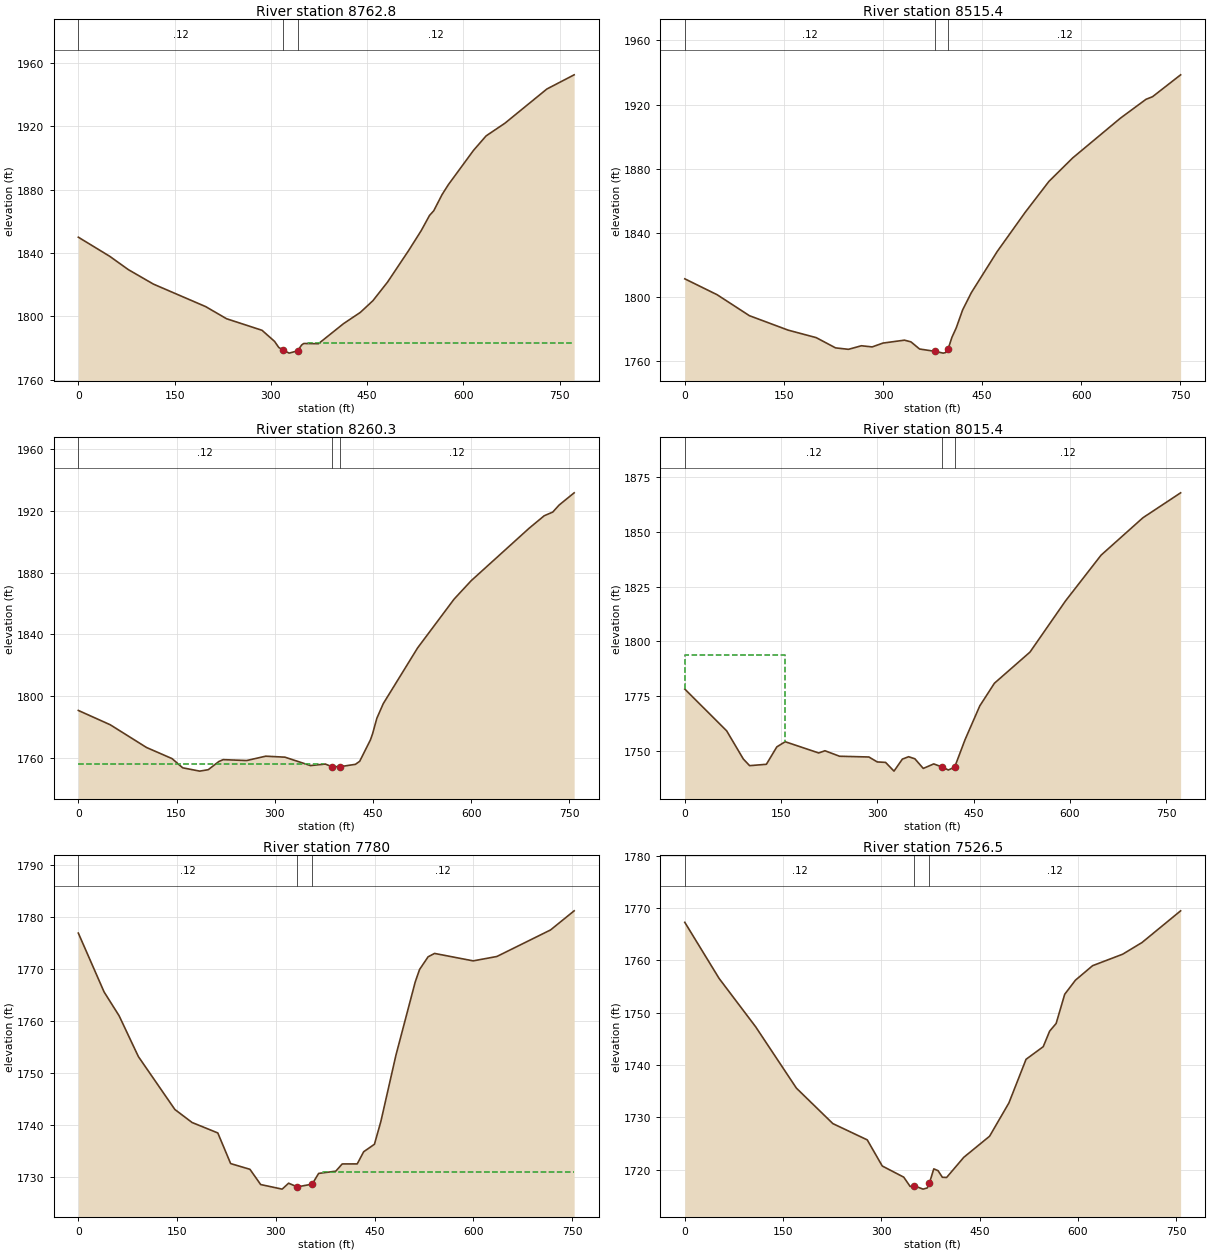
Type RM Length L Ch R = 1 ,8762.8  ,241,247.4,250
XS GIS Cut Line= 3
     2078178.684      249155.093     2078134.383      249506.781
     2077946.872      249880.382
#Sta/Elev= 30
       0 1849.92    48.8  1837.9      78 1829.44   117.1 1820.31   198.4 1806.14
   230.9  1798.5   286.2  1791.2   305.7 1784.22   312.2 1780.41   318.7 1778.83
   328.4  1776.8   341.5 1778.21     348 1781.97   351.2 1782.87   374.1 1782.73
   413.2  1795.4   439.4  1802.5     459 1809.89   481.8 1821.63   514.5 1841.44
   534.1 1853.99   547.2 1863.67   553.7 1866.56   566.7 1876.79   576.5 1883.04
   615.7 1904.69   635.3 1913.81   664.7 1921.83     730 1943.39   772.5 1952.33
#Mann= 3 ,-1 , 0
       0     .12       0   318.7    .045       0   341.5     .12       0
#XS Ineff= 2 , 0
                          357.89         1783.39
Permanent Ineff=
       F       F
Bank Sta=318.7,341.5
XS Rating Curve= 0 ,0
Exp/Cntr=0.3,0.1

Type RM Length L Ch R = 1 ,8515.4  ,246.4,255,249.2
XS GIS Cut Line= 3
     2078004.415      249107.653     2077892.951       249482.47
     2077766.451      249818.571
#Sta/Elev= 30
       0  1811.4    48.9  1801.5    97.8 1788.43   156.4 1779.43   198.8 1774.77
   228.1 1768.38   247.7 1767.48   267.2  1769.7   283.5 1768.98   299.8 1771.37
   332.4 1773.19   342.2 1772.12   355.2 1767.68     378 1766.25     391 1765.11
   394.3 1765.43   397.6  1766.6   398.5 1767.76   404.1 1774.88   410.6 1780.73
   420.4 1792.06   433.5 1802.75   472.7 1828.43   515.1 1852.88     551 1872.13
   586.9 1886.72   658.8  1911.4   697.9 1923.27   707.7 1924.86   750.2  1938.5
#Mann= 3 ,-1 , 0
       0     .12       0     378    .045       0   398.5     .12       0
#XS Ineff= 2 , 0
           331.9 1773.09
Permanent Ineff=
       F       F
Bank Sta=378,398.5
XS Rating Curve= 0 ,0
Exp/Cntr=0.3,0.1

Type RM Length L Ch R = 1 ,8260.3  ,225.4,245,277.7
XS GIS Cut Line= 3
     2077894.559      249054.933     2077674.441       249361.38
     2077596.817      249733.288
#Sta/Elev= 30
       0 1790.56    48.8 1781.25   104.1 1766.52   143.1  1759.3   159.4 1753.32
   185.4 1751.17   198.4  1752.1   214.7 1757.43   221.2 1758.63     257 1758.04
   286.2 1760.87   315.5 1760.23   354.5 1754.77   377.3 1755.76   387.1 1754.05
   400.2 1754.08   423.2 1755.59   429.7 1757.56   446.1 1771.46   449.4 1775.48
   455.9 1785.49   465.7 1794.99   518.1 1831.13   573.8 1862.78     600 1874.79
   688.4  1908.8   711.4  1916.9   724.5  1919.3   734.3 1923.89   757.2  1931.8
#Mann= 3 ,-1 , 0
       0     .12       0   387.1    .045       0   400.2     .12       0
#XS Ineff= 2 , 0
           375.1 1755.91
Permanent Ineff=
       F       F
Bank Sta=387.1,400.2
XS Rating Curve= 0 ,0
Exp/Cntr=0.3,0.1

Type RM Length L Ch R = 1 ,8015.4  ,264.8,235.3,229.4
XS GIS Cut Line= 3
     2077845.727      249010.607     2077497.842      249234.749
     2077178.731      249398.214
#Sta/Elev= 30
       0 1778.22    65.2 1759.17    91.2  1746.3     101 1743.27   127.1  1743.9
   143.4 1751.86   156.4  1754.2   208.6 1749.07   218.3 1750.08   241.1 1747.57
   286.8 1747.23   299.8 1744.98   312.8 1744.76   325.9 1740.78   338.9 1746.26
   348.7 1747.36   358.4 1746.41   371.5 1742.01   387.8 1744.07   400.8 1742.67
   410.6  1741.3   420.4 1742.61   436.7 1755.22   459.5 1770.53   482.3 1780.88
   537.7 1795.09   593.1 1818.46   648.5 1839.34   713.7 1856.41   772.4 1867.78
#Mann= 3 ,-1 , 0
       0     .12       0   400.8    .045       0   420.4     .12       0
#XS Ineff= 2 , 0
          156.37 1793.75
Permanent Ineff=
       F       F
Bank Sta=400.8,420.4
XS Rating Curve= 0 ,0
Exp/Cntr=0.3,0.1

Type RM Length L Ch R = 1 ,7780    ,219.2,253.5,256.2
XS GIS Cut Line= 3
     2077802.913      248842.282     2077433.122      249041.935
     2077106.685      249105.963
#Sta/Elev= 30
       0 1776.82    39.1 1765.51    61.9 1760.93    91.2 1753.08   146.6 1742.91
   172.7 1740.41   211.8  1738.4   231.3 1732.51   260.6 1731.41   276.9 1728.48
   309.5  1727.6   319.3 1728.74   332.3 1728.03   355.1 1728.56   364.9 1730.62
   390.9 1731.05   400.7 1732.44   423.5 1732.45   433.3 1734.79   449.6 1736.22
   459.4 1740.61   482.2 1753.31   511.6 1767.44   518.1 1769.81   531.1 1772.26
   540.9 1772.91   599.6 1771.48   635.5 1772.32     717 1777.42   752.9  1781.1
#Mann= 3 ,-1 , 0
       0     .12       0   332.3    .045       0   355.1     .12       0
#XS Ineff= 2 , 0
                          371.63         1730.89
Permanent Ineff=
       F       F
Bank Sta=332.3,355.1
XS Rating Curve= 0 ,0
Exp/Cntr=0.3,0.1

Type RM Length L Ch R = 1 ,7526.5  ,329.1,322.3,313.9
XS GIS Cut Line= 2
     2077738.677       248651.31     2077072.377      249010.725
#Sta/Elev= 30
       0 1767.28    52.4 1756.56   108.2 1747.32   170.4  1735.6   226.1 1728.82
   278.6 1725.71   301.5 1720.72   334.3 1718.59   344.1 1716.81   350.5 1716.94
   363.8  1716.3   370.3 1716.53   373.6  1717.5   380.2 1720.17   386.7 1719.83
   393.3 1718.56   399.8 1718.53     426 1722.38   465.4 1726.41   494.9 1732.77
   521.1 1741.11   547.3 1743.52   557.1 1746.49     567 1747.95   580.1 1753.53
   596.5 1756.23   622.7    1759   668.6 1761.19   698.1 1763.42   757.1 1769.48
#Mann= 3 ,-1 , 0
       0     .12       0   350.5    .045       0   373.6     .12       0
Bank Sta=350.5,373.6
XS Rating Curve= 0 ,0
Exp/Cntr=0.3,0.1

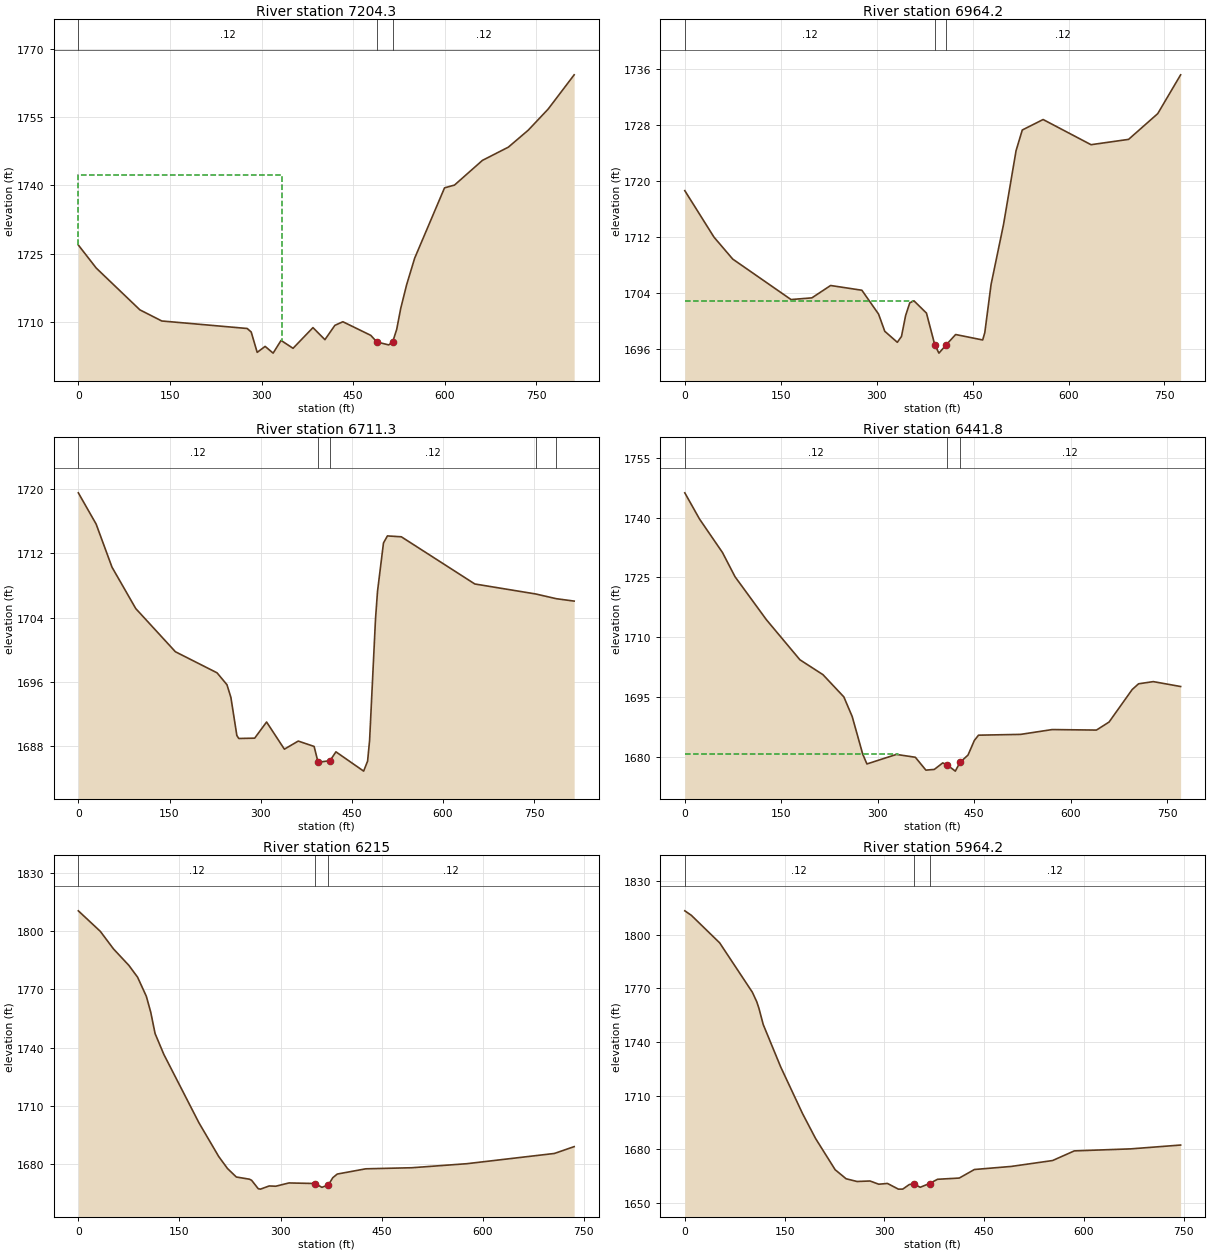
Type RM Length L Ch R = 1 ,7204.3  ,214.7,240.1,268.3
XS GIS Cut Line= 3
     2077608.469      248470.755     2077339.372      248491.588
     2076927.913      248844.019
#Sta/Elev= 30
       0 1726.93    29.3 1721.87   100.8 1712.69   136.6 1710.25   276.4  1708.6
     283 1707.83   292.8 1703.36   305.8 1704.67   318.9 1703.19   331.9 1705.98
   351.5 1704.25   384.1 1708.79   403.7 1706.15     420 1709.29   433.1 1710.08
   478.8 1707.09   488.7 1705.64   508.2 1704.99   514.7 1705.69   521.2 1708.41
   527.7 1712.96   537.5 1718.23   550.6 1724.04   599.5 1739.48   615.8 1740.09
   661.5 1745.51     704 1748.42   736.6 1752.15   769.2 1756.79   811.7  1764.3
#Mann= 3 ,-1 , 0
       0     .12       0   488.7    .045       0   514.7     .12       0
#XS Ineff= 2 , 0
          332.91 1742.23
Permanent Ineff=
       F       F
Bank Sta=488.7,514.7
XS Rating Curve= 0 ,0
Exp/Cntr=0.3,0.1

Type RM Length L Ch R = 1 ,6964.2  ,235.4,252.9,264.5
XS GIS Cut Line= 3
     2077581.406      248402.395     2077181.092      248419.539
     2076807.271      248394.646
#Sta/Elev= 30
       0 1718.65    45.6 1712.01    74.9 1708.87   166.1 1703.08   198.7 1703.32
     228 1705.09   276.9 1704.41     303    1701   312.7 1698.54   332.3 1696.97
   338.8  1697.8   345.3  1700.8   351.8 1702.61   358.3  1702.9   377.9 1701.14
   390.9  1696.6   397.4 1695.42   408.2 1696.55   423.5 1698.08   465.8  1697.3
   469.1 1698.35   478.9 1705.23   498.4 1713.82     518 1724.37   527.7 1727.32
   560.3 1728.82   635.2 1725.22   693.9 1725.98   739.5 1729.66   775.3 1735.21
#Mann= 3 ,-1 , 0
       0     .12       0   390.9    .045       0   408.2     .12       0
#XS Ineff= 2 , 0
          356.12 1702.88
Permanent Ineff=
       F       F
Bank Sta=390.9,408.2
XS Rating Curve= 0 ,0
Exp/Cntr=0.3,0.1

Type RM Length L Ch R = 1 ,6711.3  ,248.2,269.6,280.7
XS GIS Cut Line= 3
     2077599.788      248366.588     2077146.663      248158.255
     2076945.274      247913.463
#Sta/Elev= 30
       0 1719.52    29.3 1715.63    55.4 1710.27    94.5 1705.12   159.7 1699.75
   228.2 1697.13   244.5 1695.65     251 1694.07   260.8 1689.33     264 1688.96
   290.1    1689   309.7 1691.01     339 1687.63   361.8 1688.64   387.9 1687.97
   394.4    1686     414  1686.2   423.8  1687.3   469.4  1684.9   475.9 1686.15
   479.2 1688.75   488.9 1703.83   492.2 1707.26     502 1713.28   508.5 1714.16
   531.4 1714.05   652.3 1708.18  752.391706.939   786.3 1706.35   815.7 1706.05
#Mann= 5 ,-1 , 0
       0     .12       0   394.4    .045       0     414     .12       0
  752.39     .06       0   786.3     .12       0
Bank Sta=394.4,414
XS Rating Curve= 0 ,0
Exp/Cntr=0.3,0.1

Type RM Length L Ch R = 1 ,6441.8  ,248.5,226.8,209.2
XS GIS Cut Line= 3
     2077743.886      248201.657     2077499.094      248113.116
     2077134.511      247755.477
#Sta/Elev= 30
       0 1746.22    22.8 1739.67    58.6 1731.24    78.1 1725.17   126.9 1714.38
     179 1704.33   214.8  1700.6   247.3 1695.02   260.3 1690.09   276.7 1680.64
   283.2 1678.19   329.1 1680.58   358.5 1679.87   374.9 1676.64     388 1676.82
   401.1 1678.45   407.6 1677.99   420.7 1676.39   427.8 1678.56   440.4 1680.42
   450.2 1684.07   456.7 1685.41   522.2 1685.61   571.3 1686.82   640.1 1686.69
   659.7  1688.7   695.7 1696.87   705.6  1698.3   728.5 1698.85     771 1697.62
#Mann= 3 ,-1 , 0
       0     .12       0   407.6    .045       0   427.8     .12       0
#XS Ineff= 2 , 0
           331.9 1680.71
Permanent Ineff=
       F       F
Bank Sta=407.6,427.8
XS Rating Curve= 0 ,0
Exp/Cntr=0.3,0.1

Type RM Length L Ch R = 1 ,6215    ,257,250.8,245.4
XS GIS Cut Line= 3
     2077876.987      247929.405      2077500.83      247837.074
     2077196.732      247667.329
#Sta/Elev= 30
       0 1810.34    32.6  1799.8    52.1 1790.79    74.9 1782.34    87.9 1776.24
   100.9 1766.41   107.4 1758.28   113.9 1747.23   126.9 1736.53     179 1701.36
   208.3 1684.06   221.3  1677.9   234.4 1673.54   253.9 1672.41   257.1 1671.84
   266.9 1667.53   270.2 1667.31   283.2 1668.94   292.9  1668.8   312.5 1670.49
   351.5 1670.19   361.3 1668.23   370.9 1669.47   377.6 1673.21   384.1 1675.05
   426.4 1677.75   494.7  1678.3   576.1 1680.37   706.3 1685.64   735.6 1689.15
#Mann= 3 ,-1 , 0
       0     .12       0   351.5    .045       0   370.9     .12       0
Bank Sta=351.5,370.9
XS Rating Curve= 0 ,0
Exp/Cntr=0.3,0.1

Type RM Length L Ch R = 1 ,5964.2  ,243.3,250,245.4
XS GIS Cut Line= 3
     2077984.121      247645.441     2077624.787      247618.822
     2077248.491      247538.066
#Sta/Elev= 30
       0 1813.34     9.8 1810.84    52.4 1795.43   101.5 1767.85   108.1 1762.55
   111.4 1758.87   117.9 1749.74   144.1 1726.08   176.9    1700   196.5 1686.06
     226 1668.55   242.4 1663.52   258.8 1661.98   278.4 1662.26   291.5 1660.46
   304.6 1660.89     321 1657.71   327.6 1657.72   337.4 1660.28   343.9 1660.68
   353.8 1658.75   367.8 1660.85   379.9 1663.22   412.5  1663.9   435.3 1668.68
   490.8 1670.41   552.8  1673.7   585.4 1679.09   670.2 1680.22   745.2 1682.36
#Mann= 3 ,-1 , 0
       0     .12       0   343.9    .045       0   367.8     .12       0
Bank Sta=343.9,367.8
XS Rating Curve= 0 ,0
Exp/Cntr=0.3,0.1

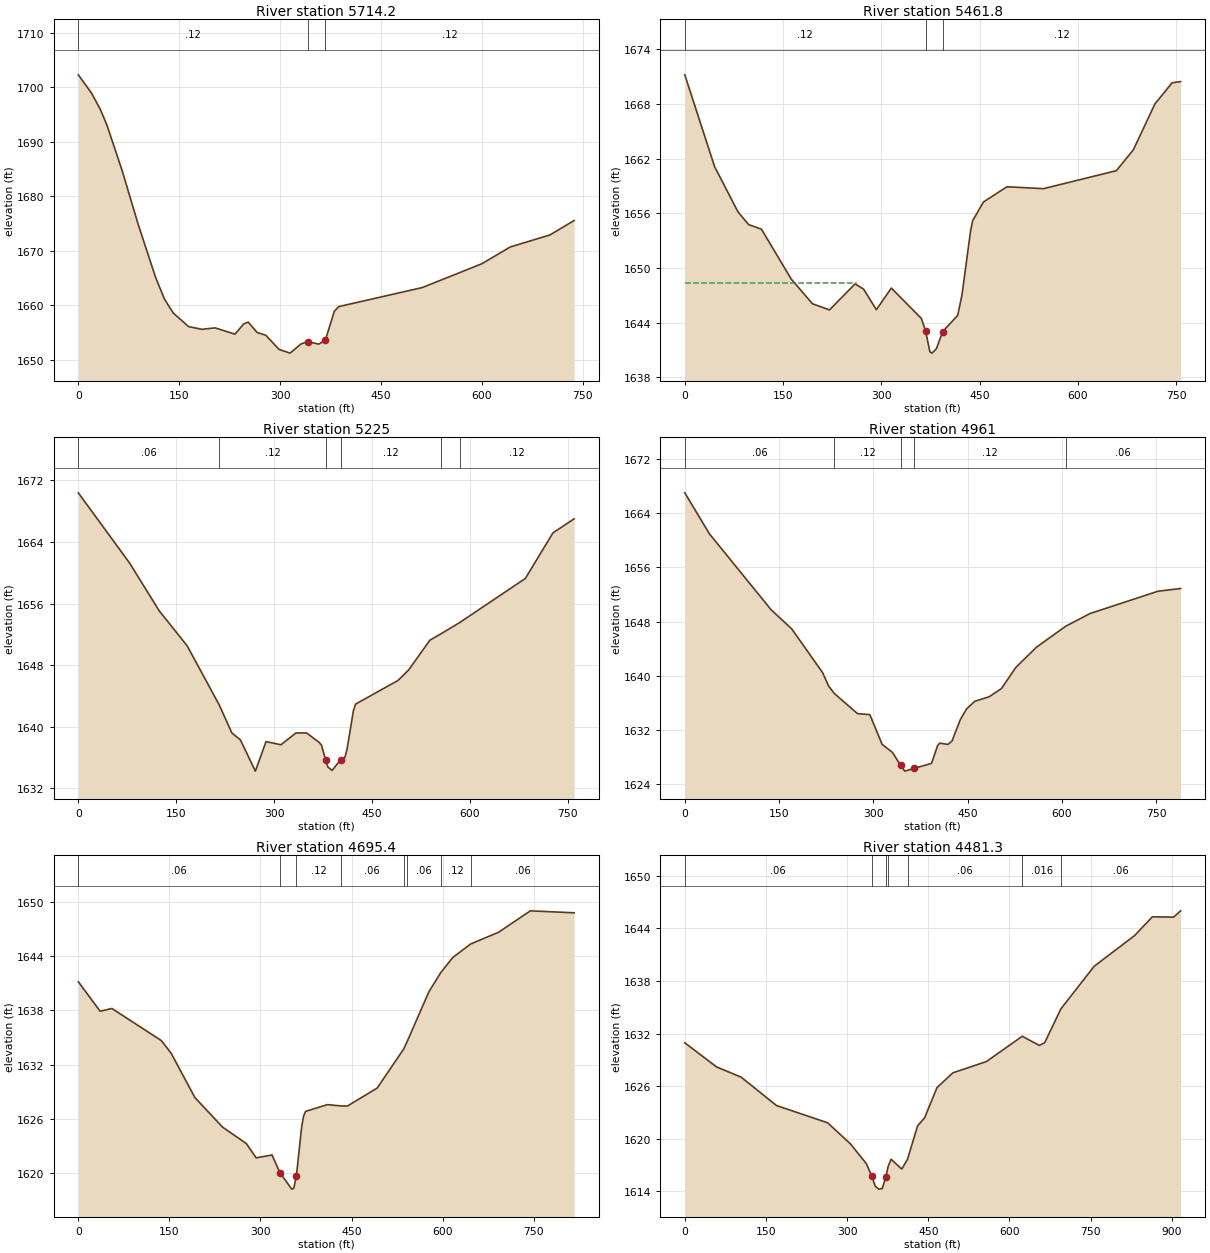
Type RM Length L Ch R = 1 ,5714.2  ,255.2,252.4,249.7
XS GIS Cut Line= 3
     2077988.724      247449.825     2077630.682      247383.408
     2077262.237      247324.739
#Sta/Elev= 30
       0 1702.28    19.7 1698.91    32.8 1695.92    42.6 1693.04    65.6 1684.54
    88.6 1675.01   114.8 1665.17   127.9  1661.2   141.1 1658.61     164 1656.11
   183.7 1655.62   203.4 1655.88   232.9 1654.73     246 1656.62   252.6 1656.94
   265.7 1655.05   278.8 1654.52   298.5 1651.93   314.9 1651.25   331.3 1652.95
   341.2 1653.34   357.6  1652.9   367.4 1653.66   380.5 1658.89   387.1 1659.78
   511.4 1663.27   599.8 1667.63   642.3 1670.72   701.2 1672.92   737.2 1675.57
#Mann= 3 ,-1 , 0
       0     .12       0   341.2    .045       0   367.4     .12       0
Bank Sta=341.2,367.4
XS Rating Curve= 0 ,0
Exp/Cntr=0.3,0.1

Type RM Length L Ch R = 1 ,5461.8  ,245.8,236.8,226.8
XS GIS Cut Line= 3
     2078033.816      247192.977     2077735.205      247147.838
     2077282.647      247106.203
#Sta/Elev= 30
       0 1671.18    45.5 1661.11    81.2 1656.15    97.4 1654.76   116.9 1654.26
   162.4 1648.79   194.8 1646.08   220.8 1645.41   259.8 1648.26   272.8 1647.69
   292.3 1645.43   315.1  1647.8   360.9 1644.48   367.4  1643.1   373.9 1640.83
   377.2 1640.67   383.7 1641.13   393.6 1643.04   416.4 1644.81     423 1647.09
   436.1 1654.13   439.3  1655.2   455.7 1657.24   491.6 1658.91   547.2  1658.7
   658.4 1660.67   684.5 1662.97   717.2 1667.98   743.4  1670.3   756.5 1670.44
#Mann= 3 ,-1 , 0
       0     .12       0   367.4    .045       0   393.6     .12       0
#XS Ineff= 2 , 0
          261.29 1648.35
Permanent Ineff=
       F       F
Bank Sta=367.4,393.6
XS Rating Curve= 0 ,0
Exp/Cntr=0.3,0.1

Type RM Length L Ch R = 1 ,5225    ,245.2,264.1,281.7
XS GIS Cut Line= 3
     2078009.511      246849.227     2077580.691      246920.407
     2077275.963      247033.688
#Sta/Elev= 30
       0 1670.36    78.4 1661.27   124.2 1655.02   166.7 1650.52  215.881642.849
   235.3  1639.2   248.4  1638.3   271.3 1634.25   287.6 1638.08   310.5 1637.67
   333.4  1639.2   349.7 1639.21   369.3 1637.96   372.6 1637.63   379.1 1635.65
   382.4 1634.79   388.9 1634.34     402 1635.74   408.5 1636.03   411.8  1637.1
   421.6 1642.13   424.9 1642.95     490 1646.02   506.2 1647.38   538.7 1651.24
  556.081652.087  584.621653.538     685 1659.25   727.3 1665.16   759.8 1666.99
#Mann= 6 ,-1 , 0
       0     .06       0  215.88     .12       0   379.1    .045       0
     402     .12       0  556.08     .06       0  584.62     .12       0
Bank Sta=379.1,402
XS Rating Curve= 0 ,0
Exp/Cntr=0.3,0.1

Type RM Length L Ch R = 1 ,4961    ,283.1,265.6,244
XS GIS Cut Line= 3
     2078005.279      246815.618     2077610.205      246677.352
     2077240.462       246694.82
#Sta/Elev= 30
       0 1667.04    39.2 1660.97   137.3 1649.74     170 1646.92   219.1 1640.45
   228.9 1638.43   237.91637.343   274.7 1634.37   294.3 1634.22   313.9 1629.82
   330.3 1628.63   343.4  1626.7   349.9 1625.86     365 1626.27   392.4 1627.01
   402.2 1629.65   405.5    1630   418.6 1629.81   425.1 1630.32   438.2 1633.47
     448 1635.04   461.2 1636.19   484.1 1636.86   503.7 1638.08   526.7 1641.22
   559.4  1644.2  605.771647.289   644.6 1649.18   752.7 1652.48   788.7 1652.88
#Mann= 5 ,-1 , 0
       0     .06       0   237.9     .12       0   343.4    .045       0
     365     .12       0  605.77     .06       0
Bank Sta=343.4,365
XS Rating Curve= 0 ,0
Exp/Cntr=0.3,0.1

Type RM Length L Ch R = 1 ,4695.4  ,213.3,214.2,217.5
XS GIS Cut Line= 3
     2078007.774      246396.102     2077631.038      246451.657
     2077233.637      246630.504
#Sta/Elev= 30
       0 1641.19    35.8 1637.92    55.3 1638.22   136.7 1634.66     153 1633.24
     192 1628.33   237.6 1625.05   276.7 1623.23   292.9 1621.64     319 1621.96
     332    1620   351.5 1618.17   354.8 1618.26   359.2 1619.68   367.8 1625.07
     371 1626.28   374.3  1626.8   410.3 1627.55   432.51627.404   443.1 1627.39
   492.2 1629.39  535.711633.707  541.051634.469   577.4 1640.08  597.131642.223
   616.7 1643.88  646.221645.381   692.1 1646.68   744.5 1649.06   816.6 1648.84
#Mann= 8 ,-1 , 0
       0     .06       0     332    .045       0   359.2     .12       0
   432.5     .06       0  535.71     .12       0  541.05     .06       0
  597.13     .12       0  646.22     .06       0
Bank Sta=332,359.2
XS Rating Curve= 0 ,0
Exp/Cntr=0.3,0.1

Type RM Length L Ch R = 1 ,4481.3  ,275.9,248.6,218.4
XS GIS Cut Line= 3
     2078010.052      246185.413     2077591.108      246248.532
     2077220.327      246572.921
#Sta/Elev= 30
       0 1630.95    58.7  1628.2   104.3 1627.02   169.5 1623.79     264 1621.82
   306.4  1619.4   335.7 1617.14   345.5 1615.74     352 1614.58   358.5 1614.25
   364.9 1614.32   371.5 1615.63  375.721616.821   381.3 1617.66   400.9 1616.54
  411.561617.654   430.2 1621.47   443.2 1622.39   466.1 1625.84   495.4 1627.52
   557.4 1628.81  623.631631.694   655.3 1630.65   665.1 1630.96  694.941634.813
   756.5 1639.68   831.5  1643.2   864.1 1645.33   903.3 1645.29   916.3 1646.01
#Mann= 7 ,-1 , 0
       0     .06       0   345.5    .045       0   371.5     .06       0
  375.72    .016       0  411.56     .06       0  623.63    .016       0
  694.94     .06       0
Bank Sta=345.5,371.5
XS Rating Curve= 0 ,0
Exp/Cntr=0.3,0.1