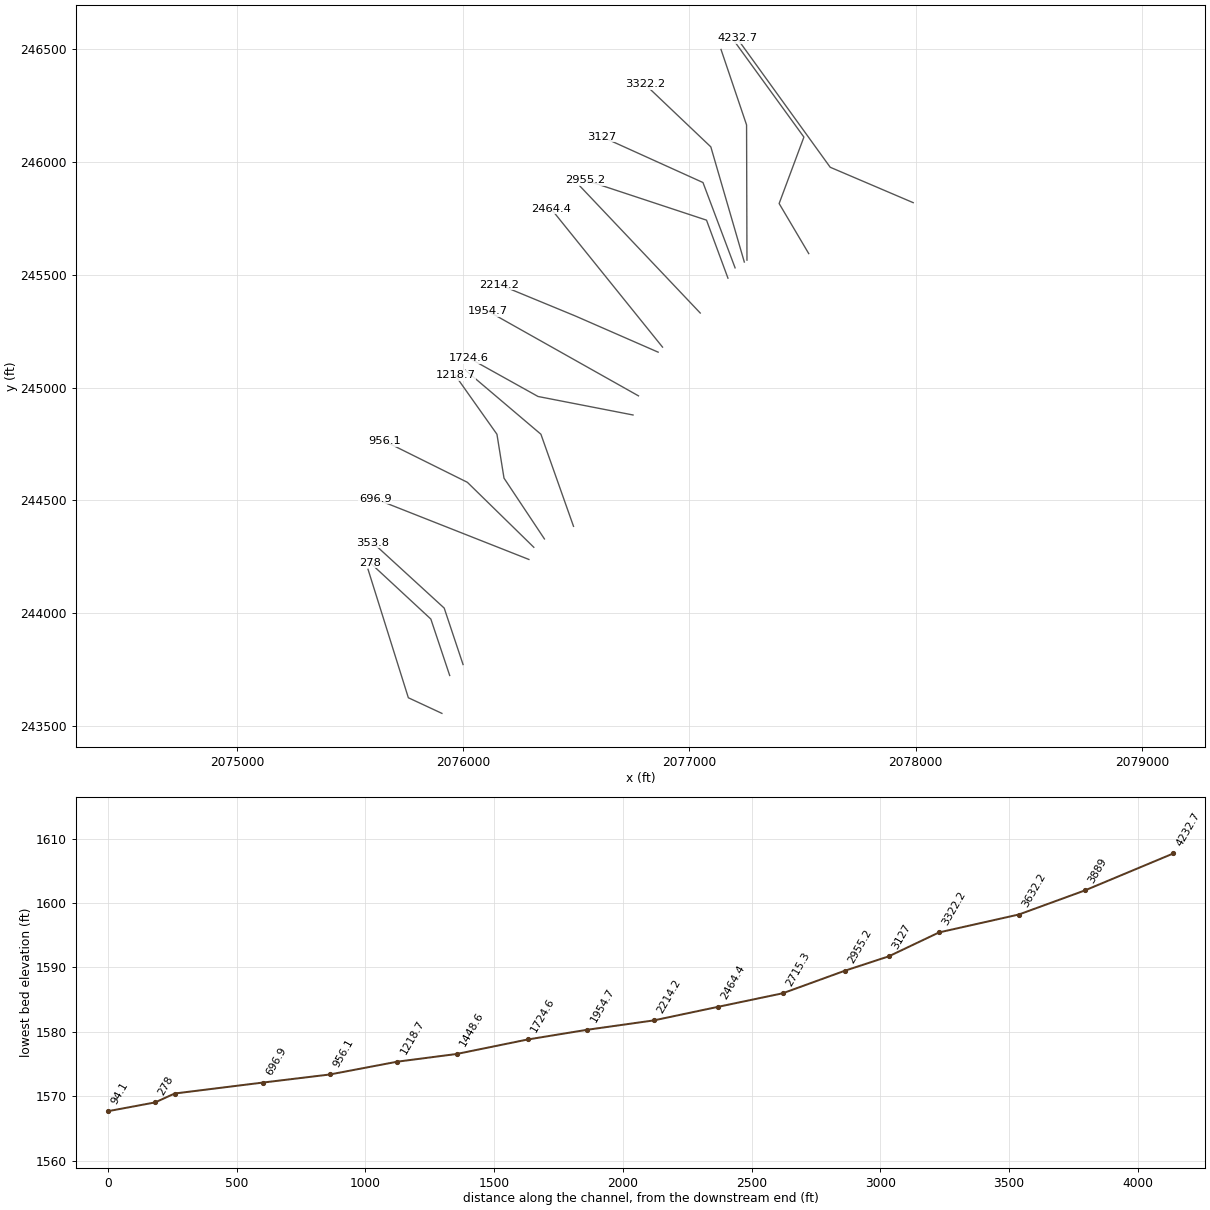
HEC-RAS study LAURELCK4.prj: LAURELCK4

--- LAURELCK4.g01 (geometry) --- (continued)

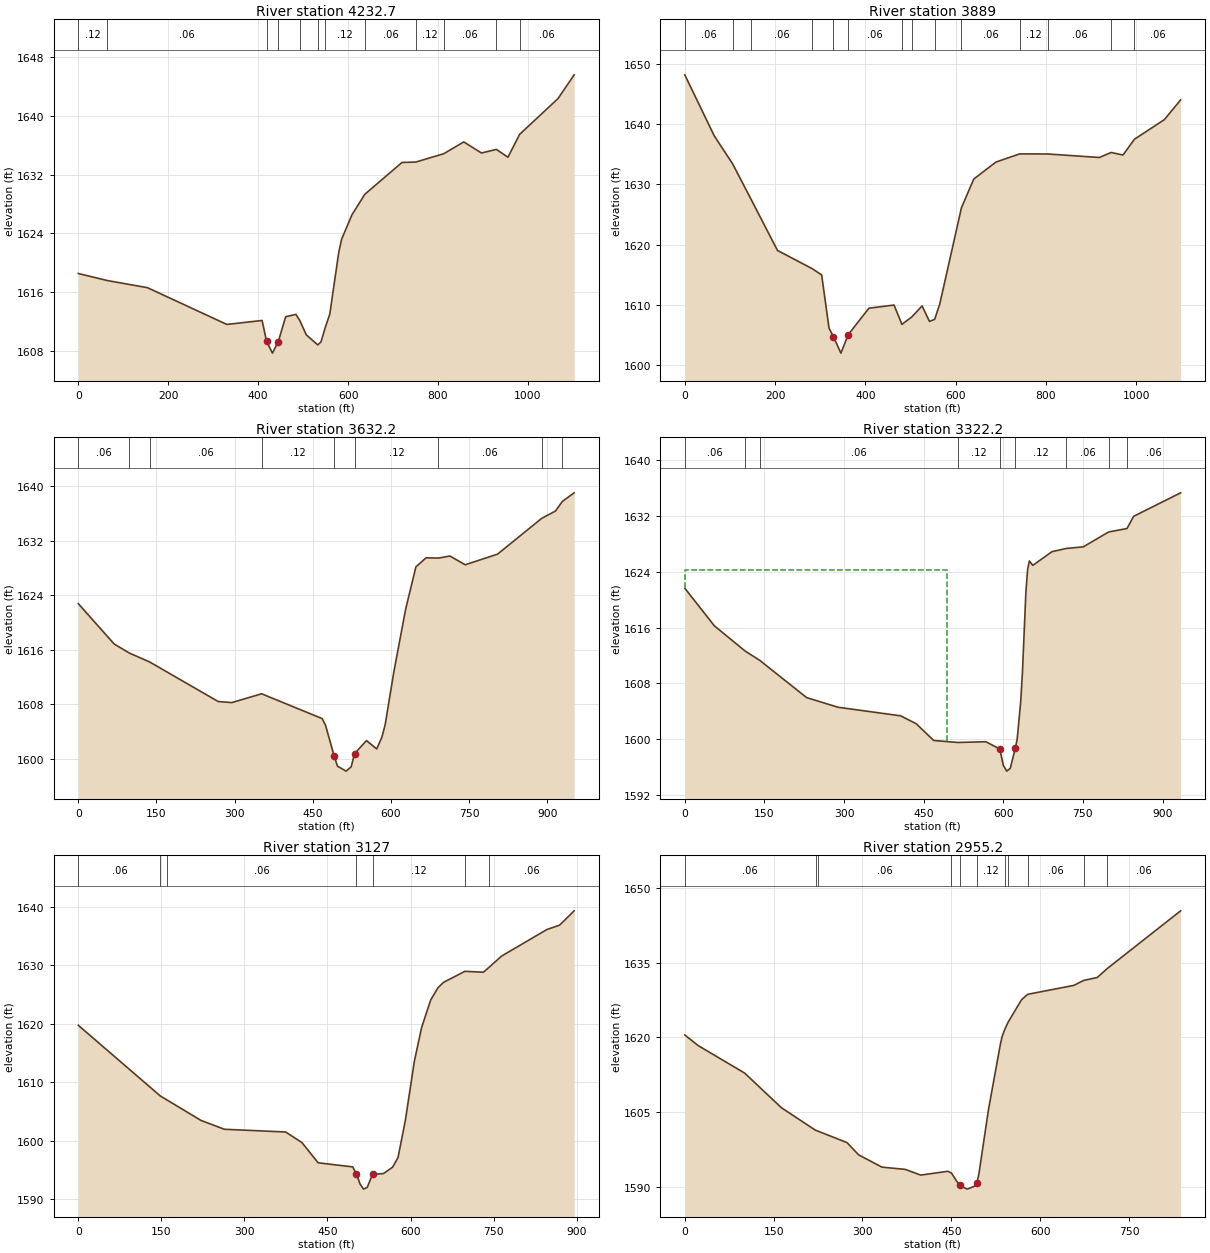
Type RM Length L Ch R = 1 ,4232.7  ,382.7,343.7,302.8
XS GIS Cut Line= 3
     2077989.219      245819.093     2077622.358      245975.963
     2077210.899      246547.144
#Sta/Elev= 30
       0 1618.55   64.811617.585   153.7 1616.62   330.3 1611.61   408.8 1612.15
   418.6 1609.33   431.7  1607.7   444.8 1609.27   461.2 1612.66   484.1 1612.98
  492.941612.103     507  1610.2  532.621608.816   539.8 1609.24  549.731611.278
   559.4 1613.03   579.1 1621.37   585.6 1623.21   608.5 1626.53  637.281629.345
   719.9 1633.68  750.661633.735  812.931634.873   857.4 1636.48   896.7 1634.97
  930.07 1635.46   955.6 1634.39  981.611637.507  1066.9 1642.38  1102.9 1645.62
#Mann= 12 ,-1 , 0
       0     .12       0   64.81     .06       0   418.6    .045       0
   444.8     .06       0  492.94    .016       0  532.62     .06       0
  549.73     .12       0  637.28     .06       0  750.66     .12       0
  812.93     .06       0  930.07    .016       0  981.61     .06       0
Bank Sta=418.6,444.8
XS Rating Curve= 0 ,0
Exp/Cntr=0.3,0.1

Type RM Length L Ch R = 1 ,3889    ,235.4,256.7,270.4
XS GIS Cut Line= 4
     2077527.413      245593.399      2077396.57      245815.212
     2077506.038      246109.644     2077197.011      246536.727
#Sta/Elev= 30
       0 1648.19    65.2 1638.06  106.071633.393   147.31627.447   205.4 1619.02
  282.451615.988   303.3 1614.95   319.7 1606.08   329.5 1604.69   345.9 1601.96
   362.2 1605.03     408 1609.42   463.7 1609.95  481.181606.741  503.111607.976
   525.8  1609.8   542.2 1607.23  553.721607.569   565.1 1610.14  613.081626.106
   640.4 1630.88   689.5  1633.7  742.241635.058  804.471635.041   918.7 1634.46
  944.841635.291   971.1 1634.87  996.421637.487  1062.8 1640.75  1098.8 1644.03
#Mann= 14 ,-1 , 0
       0     .06       0  106.07     .12       0   147.3     .06       0
  282.45     .12       0   329.5    .045       0   362.2     .06       0
  481.18    .016       0  503.11     .06       0  553.72     .12       0
  613.08     .06       0  742.24     .12       0  804.47     .06       0
  944.84    .016       0  996.42     .06       0
Bank Sta=329.5,362.2
XS Rating Curve= 0 ,0
Exp/Cntr=0.3,0.1

Type RM Length L Ch R = 1 ,3632.2  ,271.6,310,331
XS GIS Cut Line= 3
     2077254.302      245564.505     2077252.566      246163.463
     2077139.634      246497.752
#Sta/Elev= 30
       0 1622.75    68.7 1616.85   98.011615.517  137.131614.203   268.4 1608.42
   294.6 1608.26  351.85 1609.55     468 1605.92   474.6 1604.92     491 1600.47
   497.5 1598.95   513.9 1598.22   523.7 1598.84   530.2 1600.77   553.1  1602.7
   572.8 1601.47   582.6 1603.16   589.1 1605.06   605.5 1612.69   628.4 1621.97
     648 1628.14   667.6 1629.47  691.23 1629.43   713.3 1629.73   742.7 1628.45
   804.8 1630.01  889.211635.233   915.9 1636.32  929.221637.739   951.8 1638.99
#Mann= 9 ,-1 , 0
       0     .06       0   98.01     .12       0  137.13     .06       0
  351.85     .12       0     491    .045       0   530.2     .12       0
  691.23     .06       0  889.21    .016       0  929.22     .06       0
Bank Sta=491,530.2
XS Rating Curve= 0 ,0
Exp/Cntr=0.3,0.1

Type RM Length L Ch R = 1 ,3322.2  ,182,195.2,207.2
XS GIS Cut Line= 3
     2077242.577      245556.083      2077094.58      246066.241
     2076802.913      246344.019
#Sta/Elev= 30
       0 1621.64    55.7 1616.25  113.661612.637  141.13 1611.31   229.5 1605.97
   288.6 1604.59   406.6 1603.36   436.1 1602.22   468.9 1599.83  513.971599.543
   567.2 1599.65   593.4 1598.61     600 1596.26   606.5 1595.44   613.1 1595.84
   622.9 1598.82   626.2 1600.08   632.7 1605.33     636 1609.54   642.5 1621.03
   645.8 1624.35   649.1 1625.54   655.6 1624.91   691.6 1626.87  718.821627.335
   750.6 1627.56  798.331629.692  832.921630.187   845.6 1631.94     934  1635.3
#Mann= 9 ,-1 , 0
       0     .06       0  113.66     .12       0  141.13     .06       0
  513.97     .12       0   593.4    .045       0   622.9     .12       0
  718.82     .06       0  798.33    .016       0  832.92     .06       0
#XS Ineff= 2 , 0
          494.33 1624.18
Permanent Ineff=
       F       F
Bank Sta=593.4,622.9
XS Rating Curve= 0 ,0
Exp/Cntr=0.3,0.1

Type RM Length L Ch R = 1 ,3127    ,167.5,171.8,176.4
XS GIS Cut Line= 3
     2077201.809      245530.295     2077059.858      245908.255
     2076611.941       246111.38
#Sta/Elev= 30
       0 1619.72   148.31607.631  160.141606.961   221.4 1603.48   263.7 1601.96
   374.4 1601.49   403.7  1599.7   433.2 1596.23   495.5 1595.53   502.1 1594.39
   508.7 1592.64   515.2 1591.73   521.8 1592.03   531.6 1594.27   551.3 1594.39
   567.7 1595.49   577.5 1597.14   590.6 1603.42     607  1613.6   620.1 1619.35
   636.5 1624.06   649.6 1626.13   659.5 1627.05  698.251628.944   731.6 1628.79
  742.591629.688   764.4 1631.54   846.4 1636.09   869.3 1636.83   895.6 1639.28
#Mann= 7 ,-1 , 0
       0     .06       0   148.3     .12       0  160.14     .06       0
   502.1    .045       0   531.6     .12       0  698.25    .016       0
  742.59     .06       0
Bank Sta=502.1,531.6
XS Rating Curve= 0 ,0
Exp/Cntr=0.3,0.1

Type RM Length L Ch R = 1 ,2955.2  ,257.5,239.9,220.4
XS GIS Cut Line= 3
     2077170.265      245484.665     2077075.483      245741.588
     2076540.761      245918.671
#Sta/Elev= 30
       0 1620.46    22.8 1618.32   101.1  1612.8     163 1605.85  220.731601.311
  224.471601.152   273.8 1598.84   293.5 1596.37   332.8  1593.9   372.1 1593.45
   398.3  1592.3   444.1 1593.07  449.971592.736   463.8 1590.22   476.9 1589.48
     490 1590.11   493.3 1590.77   496.5 1592.51   512.9  1605.6   532.6 1618.47
   535.8 1620.18  540.191621.577  545.521622.965   568.6 1627.56   578.91628.636
     657 1630.44  673.181631.424   696.3 1632.02  713.351633.831   837.1 1645.42
#Mann= 11 ,-1 , 0
       0     .06       0  220.73     .12       0  224.47     .06       0
  449.97     .12       0   463.8    .045       0   493.3     .12       0
  540.19     .06       0  545.52     .12       0   578.9     .06       0
  673.18    .016       0  713.35     .06       0
Bank Sta=463.8,493.3
XS Rating Curve= 0 ,0
Exp/Cntr=0.3,0.1

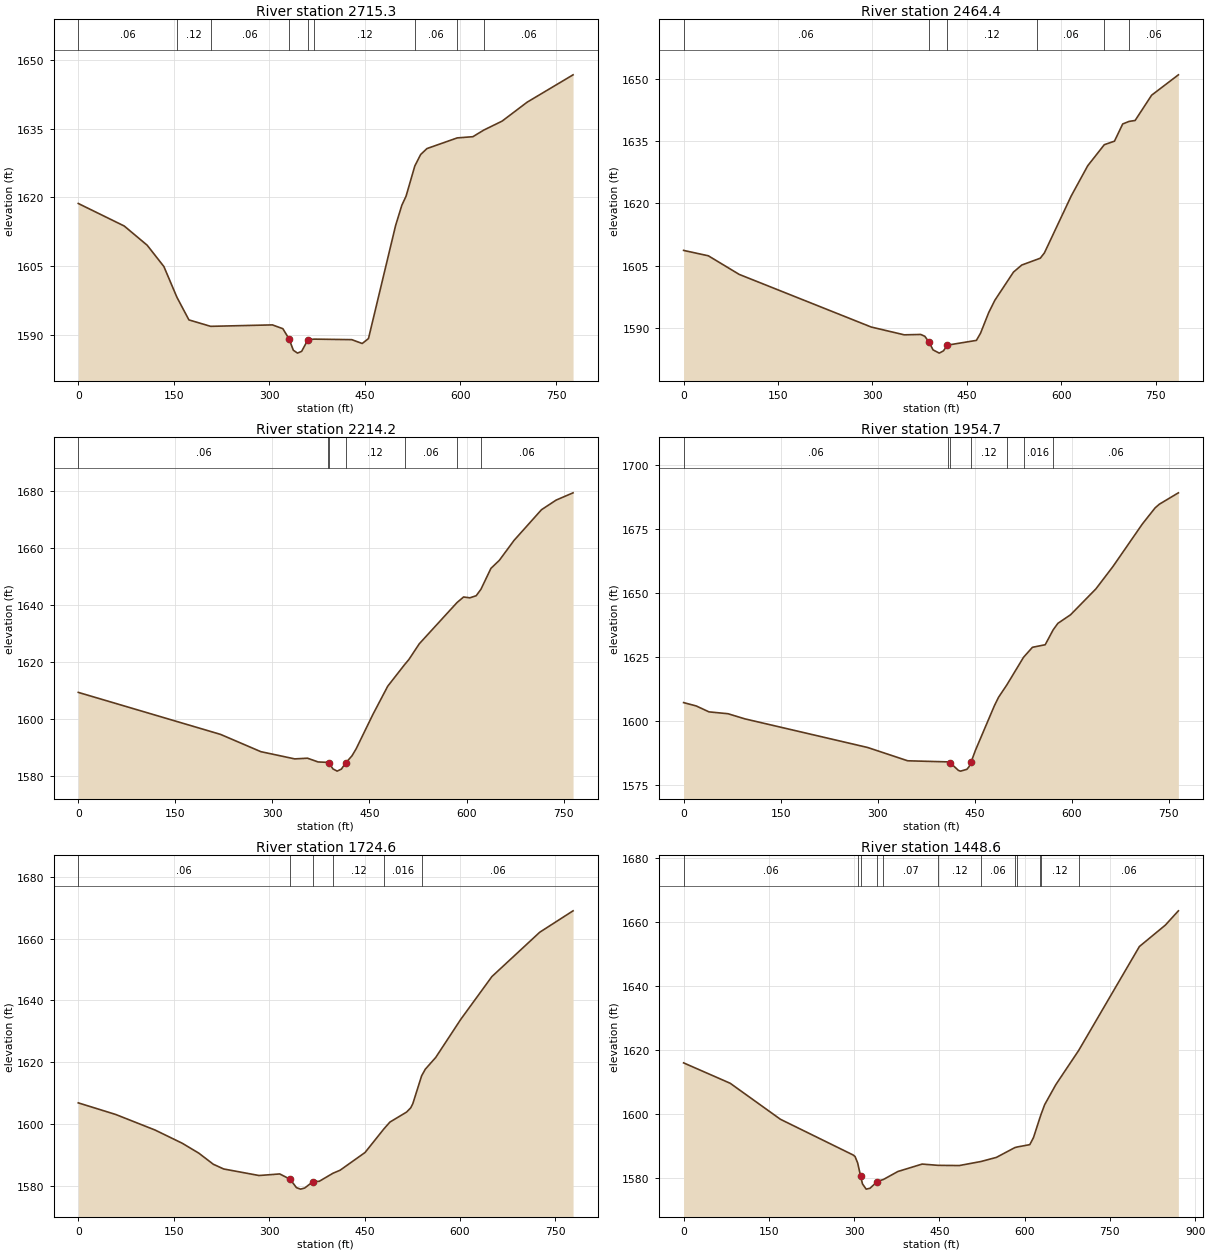
Type RM Length L Ch R = 1 ,2715.3  ,248.8,250.9,247.6
XS GIS Cut Line= 2
     2077047.705       245330.13     2076513.991      245894.539
#Sta/Elev= 30
       0 1618.65    72.1 1613.74   108.2 1609.54   134.4 1604.89   154.9 1598.18
   173.7 1593.25  207.811591.844   304.8 1592.16   321.2 1591.33     331 1589.08
   337.6 1586.64   344.2    1586   350.7 1586.39   360.5 1588.92  370.591589.054
   429.4 1588.94   445.8  1588.1   455.6 1589.18   498.2 1613.85     508 1618.27
   514.6 1620.24  528.331626.821   537.5 1629.33   547.4 1630.63  594.971632.959
   619.5 1633.22  636.711634.669   665.4 1636.62   704.7 1640.75   776.8 1646.72
#Mann= 9 ,-1 , 0
       0     .06       0   154.9     .12       0  207.81     .06       0
     331    .045       0   360.5     .06       0  370.59     .12       0
  528.33     .06       0  594.97    .016       0  636.71     .06       0
Bank Sta=331,360.5
XS Rating Curve= 0 ,0
Exp/Cntr=0.3,0.1

Type RM Length L Ch R = 1 ,2464.4  ,232.8,250.2,268.6
XS GIS Cut Line= 2
     2076881.038      245179.088     2076388.573      245791.492
#Sta/Elev= 30
       0 1608.66    39.3 1607.36    88.4 1602.87     298 1590.19   350.4 1588.31
   376.6  1588.4   383.1 1587.96   389.6 1586.59   396.2 1584.68     406  1583.9
   412.6 1584.44   419.1 1585.83     465 1586.97   471.5 1588.68   484.6 1593.68
   494.4 1596.66   523.9 1603.43     537 1605.13  560.571606.446   566.5 1606.79
     573 1608.05   615.6 1621.78   641.8 1629.06  668.131634.137   684.3 1634.99
   697.4 1639.14  707.391639.747   717.1 1639.98   743.3 1646.07   785.8 1650.98
#Mann= 6 ,-1 , 0
       0     .06       0   389.6    .045       0   419.1     .12       0
  560.57     .06       0  668.13    .016       0  707.39     .06       0
Bank Sta=389.6,419.1
XS Rating Curve= 0 ,0
Exp/Cntr=0.3,0.1

Type RM Length L Ch R = 1 ,2214.2  ,260.7,259.5,227.1
XS GIS Cut Line= 3
     2076861.572      245156.736     2076495.038       245317.24
     2076158.246      245456.425
#Sta/Elev= 30
       0 1609.39   219.8 1594.67   282.1 1588.61   334.5 1586.08   354.2 1586.32
   370.6 1585.01  386.441584.849     387  1584.8   393.6 1582.56   400.1 1581.79
   406.6 1582.51   413.2 1584.64   422.9 1587.14   429.4 1589.61   455.4 1601.71
   478.2 1611.55  504.34 1619.14   510.8 1620.88     527 1626.43  585.331640.885
   595.4 1642.82   605.1 1642.53   614.9 1643.27  622.15 1645.49   637.7 1652.86
   650.7 1655.68   673.4 1662.66   715.8 1673.41   738.5 1676.79   764.6 1679.33
#Mann= 7 ,-1 , 0
       0     .06       0  386.44     .12       0     387    .045       0
   413.2     .12       0  504.34     .06       0  585.33    .016       0
  622.15     .06       0
Bank Sta=387,413.2
XS Rating Curve= 0 ,0
Exp/Cntr=0.3,0.1

Type RM Length L Ch R = 1 ,1954.7  ,217,230.1,241.7
XS GIS Cut Line= 2
     2076774.728      244963.112     2076108.469       245338.81
#Sta/Elev= 30
       0 1607.12    19.6  1605.8    39.2  1603.5    68.6 1602.77    94.8 1600.76
   284.4 1589.58   346.5 1584.37  408.471583.945   411.9 1583.65   424.9  1580.6
   428.2 1580.33     438 1581.05   441.3 1582.09   444.6 1583.98   451.1 1588.44
   480.5 1605.93     487 1609.25  499.571613.985  525.541624.848   539.3 1628.74
     559 1629.74  571.381635.595   578.6  1638.1   598.2 1641.46   637.4 1651.58
   663.6 1660.27   709.3 1676.98   728.9 1683.24   735.5 1684.69   764.9 1689.13
#Mann= 7 ,-1 , 0
       0     .06       0  408.47     .12       0   411.9    .045       0
   444.6     .12       0  499.57     .06       0  525.54    .016       0
  571.38     .06       0
Bank Sta=411.9,444.6
XS Rating Curve= 0 ,0
Exp/Cntr=0.3,0.1

Type RM Length L Ch R = 1 ,1724.6  ,315.3,276,224.4
XS GIS Cut Line= 3
     2076750.649       244878.39     2076330.691      244960.338
     2076025.085      245130.903
#Sta/Elev= 30
       0 1606.78    58.8 1603.02   120.8 1597.97   163.3 1593.71   189.4  1590.5
   212.3 1586.89   228.6 1585.36   284.2 1583.24   316.8 1583.75   333.2 1582.01
     343 1579.31   349.5 1578.83     356 1579.19   369.1 1581.27   378.9 1581.37
  400.471583.983   411.6 1584.95   450.8 1590.69  480.521598.353     490 1600.56
   516.2  1603.8   522.7 1605.18     526 1606.53  539.771615.528   545.6 1617.69
     562  1621.5   601.2  1633.8   650.3  1647.7   725.5 1662.06   777.9    1669
#Mann= 6 ,-1 , 0
       0     .06       0   333.2    .045       0   369.1     .06       0
  400.47     .12       0  480.52    .016       0  539.77     .06       0
Bank Sta=333.2,369.1
XS Rating Curve= 0 ,0
Exp/Cntr=0.3,0.1

Type RM Length L Ch R = 1 ,1448.6  ,235.1,229.9,230.5
XS GIS Cut Line= 3
     2076487.483      244385.066     2076343.385      244793.052
     2076009.806      245076.555
#Sta/Elev= 30
       0 1616.05      82 1609.67   170.4 1598.41   298.3 1587.25   301.6 1586.79
  306.281584.744   311.4 1580.67   314.7 1578.22   321.2 1576.58   327.8 1576.84
   340.9 1578.96  351.651579.608     377 1582.09   419.6 1584.41  447.661584.017
     485 1583.95  523.141585.214   550.3  1586.5  582.991589.579   587.21589.763
   609.1 1590.49   615.6 1592.71  626.761598.829  629.39  1600.2   635.2 1602.97
   654.8 1609.22  695.231619.978   801.9 1652.42   847.6 1659.12   870.5 1663.58
#Mann= 12 ,-1 , 0
       0     .06       0  306.28     .12       0   311.4    .045       0
   340.9     .12       0  351.65     .07       0  447.66     .12       0
  523.14     .06       0  582.99     .12       0   587.2    .016       0
  626.76     .06       0  629.39     .12       0  695.23     .06       0
Bank Sta=311.4,340.9
XS Rating Curve= 0 ,0
Exp/Cntr=0.3,0.1

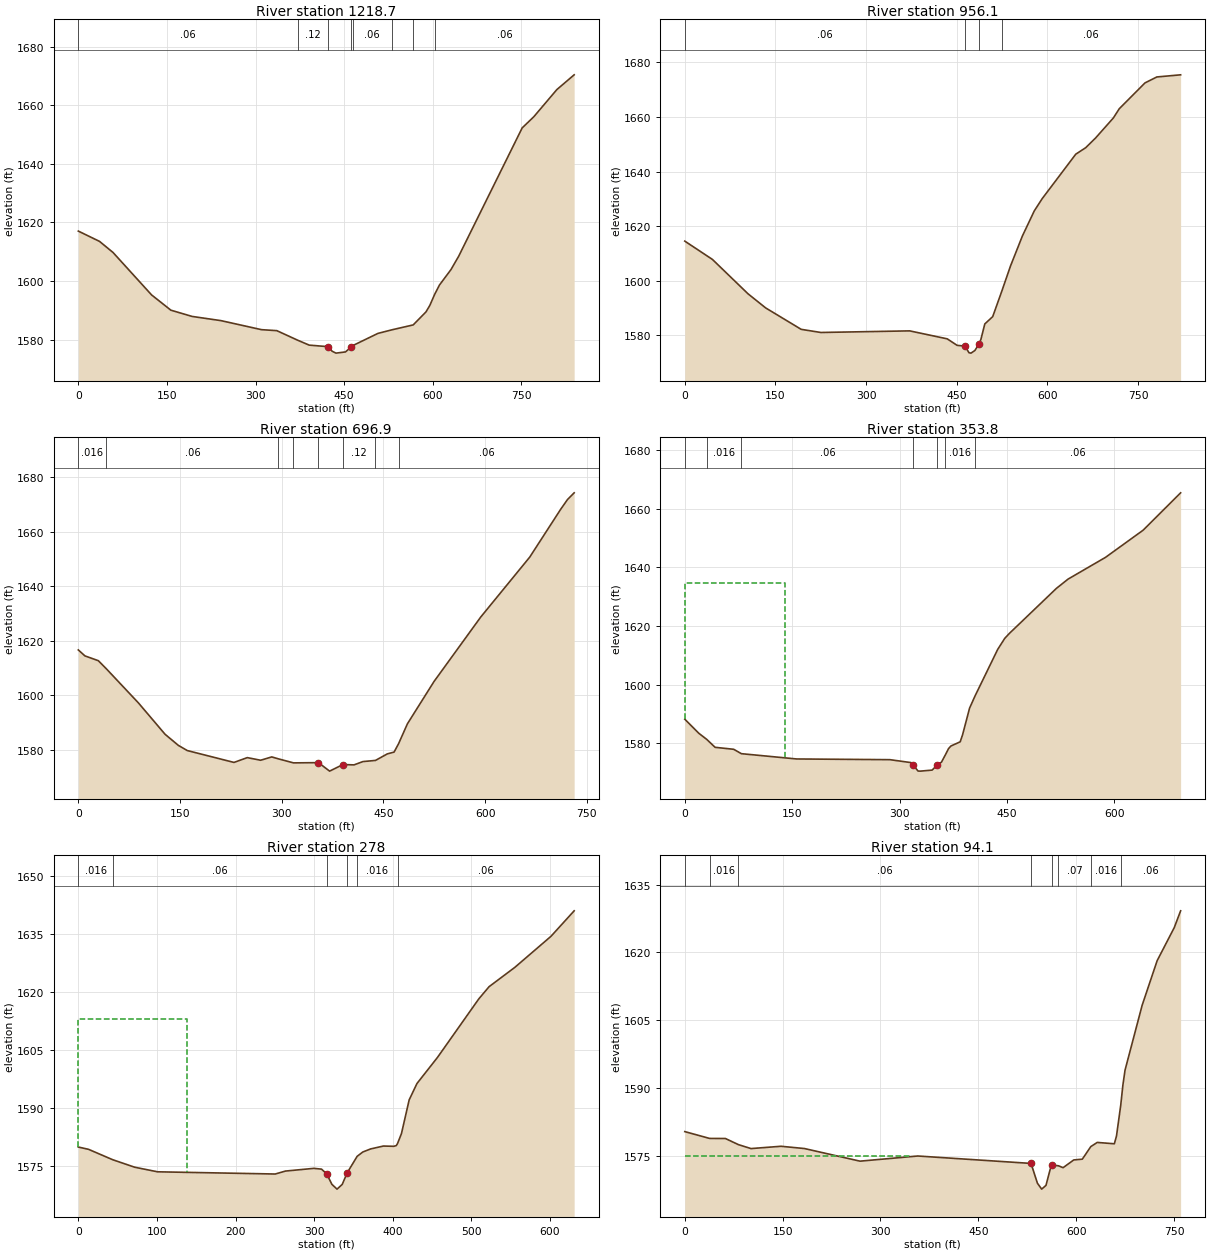
Type RM Length L Ch R = 1 ,1218.7  ,225.7,262.6,298.4
XS GIS Cut Line= 4
     2076358.873        244329.3     2076180.191      244598.607
     2076148.941      244793.052     2075964.705      245053.971
#Sta/Elev= 30
       0 1617.05    35.9 1613.54    58.8 1609.74     124 1595.27   156.7 1590.05
   192.6 1587.92   241.6 1586.48   310.1  1583.4   336.1 1583.06  372.121579.733
     391 1578.12   423.3 1577.59   429.7 1576.04   436.2 1575.39   452.3  1575.8
     462 1577.49  464.261577.921   507.2 1582.12  530.811583.342  566.971585.021
   588.6 1589.46   595.1 1591.67  603.121595.368   611.4 1598.62     631 1603.93
     644 1608.47   751.5 1652.28   771.1 1656.07   810.2 1665.36   839.5  1670.4
#Mann= 8 ,-1 , 0
       0     .06       0  372.12     .12       0   423.3    .045       0
     462     .12       0  464.26     .06       0  530.81    .016       0
  566.97     .12       0  603.12     .06       0
Bank Sta=423.3,462
XS Rating Curve= 0 ,0
Exp/Cntr=0.3,0.1

Type RM Length L Ch R = 1 ,956.1   ,257.1,259.2,252.3
XS GIS Cut Line= 3
     2076311.933      244292.214     2076018.191       244580.13
     2075651.958      244762.392
#Sta/Elev= 30
       0 1614.47    45.7 1607.76   104.5 1595.18   133.8 1589.98   192.6 1582.12
   225.2 1580.97   372.1 1581.56   434.2 1578.64   450.6 1576.25   463.7 1575.98
   470.2 1573.55   473.5  1573.4     480 1574.36   486.6 1576.72   489.9  1578.4
   496.4  1584.1   509.5 1586.79  524.34    1596     539  1605.4   558.6 1616.35
   578.2 1625.53   591.3 1630.03   646.9 1646.35   663.3 1648.72   679.7 1652.29
   709.1 1659.63   718.9 1663.02   761.5  1672.5   781.1 1674.67   820.4 1675.45
#Mann= 4 ,-1 , 0
       0     .06       0   463.7    .045       0   486.6    .016       0
  524.34     .06       0
Bank Sta=463.7,486.6
XS Rating Curve= 0 ,0
Exp/Cntr=0.3,0.1

Type RM Length L Ch R = 1 ,696.9   ,352.4,343.1,331
XS GIS Cut Line= 2
     2076290.286      244238.288     2075610.205      244507.213
#Sta/Elev= 30
       0 1616.58     9.8 1614.39    29.5 1612.64   41.431609.641    88.6 1597.17
   127.9 1585.67   147.6 1581.58   160.7 1579.69   229.6 1575.34   249.2  1577.1
   268.9 1576.14   285.3 1577.36  295.091576.651  317.351575.174   354.2 1575.26
   370.6 1572.15   390.3 1574.56   406.6 1574.44   419.8 1575.65  438.271576.073
   455.8 1578.48   465.7 1579.13  472.291582.173   485.4 1589.51   524.7 1605.04
   593.6 1628.67   665.7 1650.58   711.6 1668.21   721.5 1671.72   731.3 1674.18
#Mann= 8 ,-1 , 0
       0    .016       0   41.43     .06       0  295.09     .07       0
  317.35     .06       0   354.2    .045       0   390.3     .12       0
  438.27    .016       0  472.29     .06       0
Bank Sta=354.2,390.3
XS Rating Curve= 0 ,0
Exp/Cntr=0.3,0.1

Type RM Length L Ch R = 1 ,353.8   ,75.7,75.8,76
XS GIS Cut Line= 3
     2075999.094      243772.838     2075915.761      244022.838
     2075599.788      244312.769
#Sta/Elev= 30
       0 1588.17    19.5 1583.39   30.661581.281    42.3 1578.58    68.3  1577.9
   79.051576.403   156.2  1574.6   286.4 1574.36   315.9 1573.36   319.2 1572.42
   325.7 1570.48     329 1570.45   345.4  1570.8   351.9 1572.39   358.5 1573.54
  364.041576.082   368.3 1578.12   371.6 1579.02   384.6 1580.46   387.9 1582.85
   397.7 1591.96   405.4 1596.15     437 1612.01   446.8 1615.76   453.4 1617.48
   518.9 1632.81   535.2 1635.98   587.6 1643.42     640 1652.67   692.4 1665.43
#Mann= 7 ,-1 , 0
       0     .12       0   30.66    .016       0   79.05     .06       0
   319.2    .045       0   351.9     .12       0  364.04    .016       0
   405.4     .06       0
#XS Ineff= 2 , 0
          139.47 1634.63
Permanent Ineff=
       F       F
Bank Sta=319.2,351.9
XS Rating Curve= 0 ,0
Exp/Cntr=0.3,0.1

Type RM Length L Ch R = 1 ,278     ,199.7,184,161.9
XS GIS Cut Line= 3
     2075940.066      243724.227     2075856.733      243974.227
     2075587.636      244224.227
#Sta/Elev= 30
       0 1579.93      13 1579.34   43.811576.654    71.6 1574.73   100.8 1573.54
   250.5 1572.97   263.5 1573.73   299.6 1574.43   309.4 1574.23     316    1573
   322.6 1570.31   329.1 1569.07   335.7 1570.28   342.2 1573.33  354.721577.535
   361.9 1578.65   371.8 1579.44   388.1 1580.19   401.3 1580.12   404.5  1580.3
  406.121580.855   411.1 1583.41   420.9  1592.1   430.8 1596.32     457 1603.08
   509.5 1618.17   522.6 1621.32   555.4 1626.31   601.3 1634.31   630.8 1640.89
#Mann= 6 ,-1 , 0
       0    .016       0   43.81     .06       0     316    .045       0
   342.2     .12       0  354.72    .016       0  406.12     .06       0
#XS Ineff= 2 , 0
           137.7  1612.9
Permanent Ineff=
       F       F
Bank Sta=316,342.2
XS Rating Curve= 0 ,0
Exp/Cntr=0.3,0.1

Type RM Length L Ch R = 1 ,94.1    ,117.4,94.1,69.9
XS GIS Cut Line= 3
     2075905.621       243556.37      2075757.23      243625.619
     2075578.955      244194.713
#Sta/Elev= 30
       0 1580.41   38.051578.903    62.2 1578.89   82.191577.535   101.5 1576.66
   147.4 1577.17   183.4 1576.67   268.6 1573.88   357.1 1575.02   530.8 1573.38
   540.6    1569   547.1  1567.7   553.7 1568.53   560.2 1572.11   563.5 1573.01
  572.861572.856   579.9 1572.44   596.3 1574.15   609.4 1574.32  622.411577.098
   632.3 1578.02   658.5 1577.72   661.8 1579.45  668.311586.265   671.6  1590.7
   674.9    1594   701.1 1608.32   724.1 1618.18   750.3 1625.48   760.1  1629.2
#Mann= 8 ,-1 , 0
       0     .06       0   38.05    .016       0   82.19     .06       0
   530.8    .045       0   563.5     .12       0  572.86     .07       0
  622.41    .016       0  668.31     .06       0
#XS Ineff= 2 , 0
          343.42 1575.09
Permanent Ineff=
       F       F
Bank Sta=530.8,563.5
XS Rating Curve= 0 ,0
Exp/Cntr=0.3,0.1

Chan Stop Cuts=-1
Use User Specified Reach Order=0
Composite Channel Slope=5